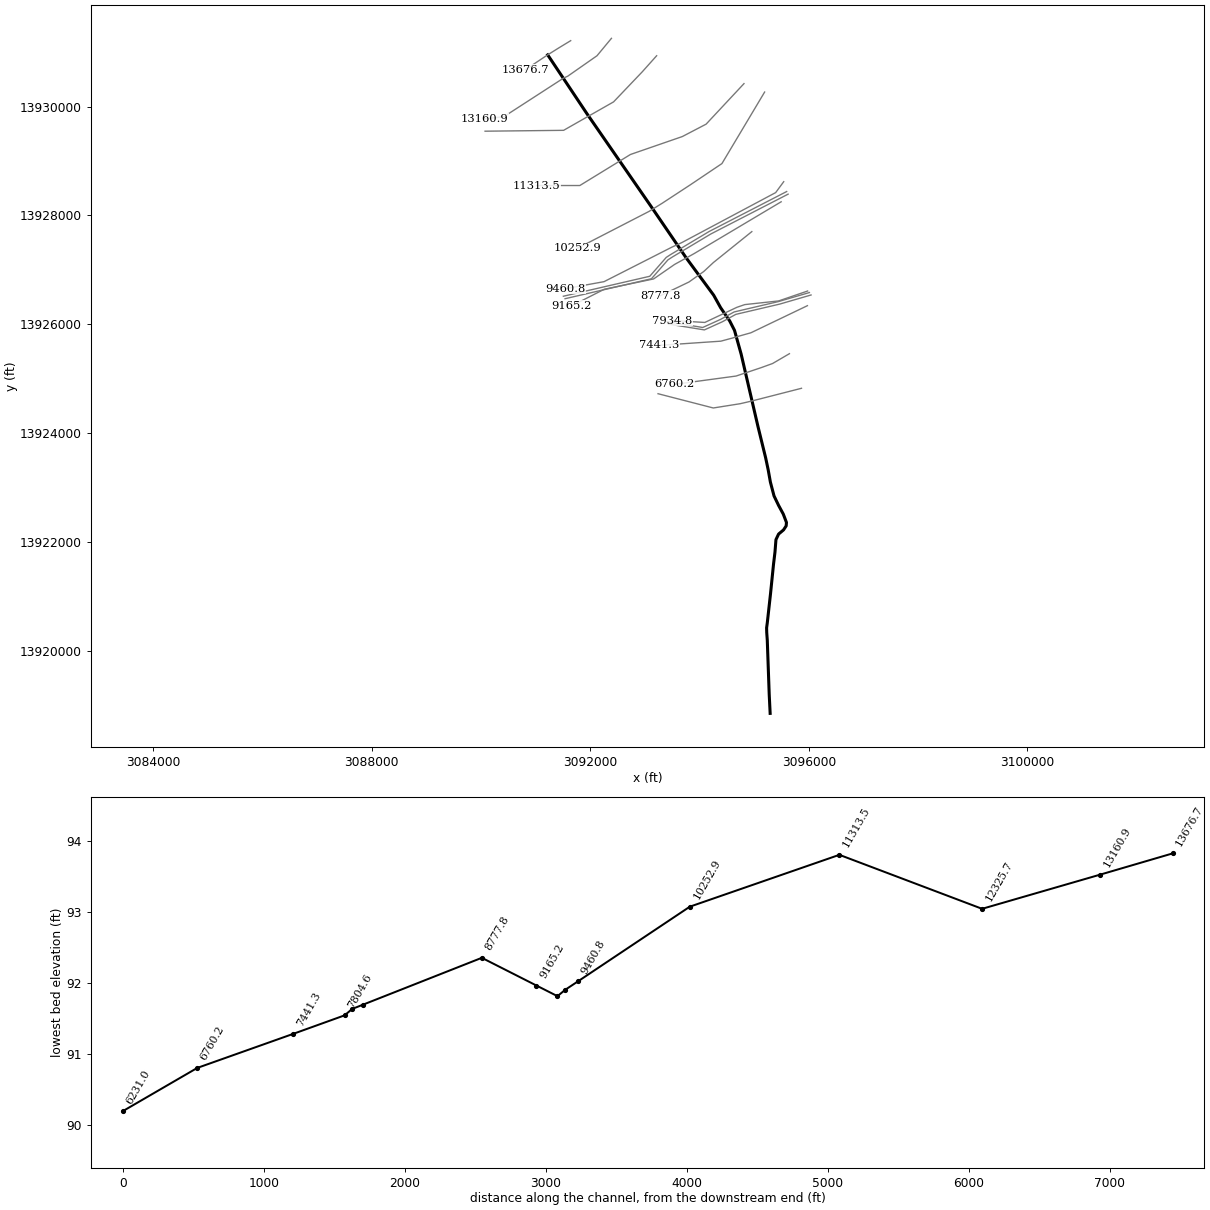
--- P145-03-00.prj (project) ---

Proj Title=P145-03-00
Current Plan=p07
Default Exp/Contr=.3,.1
English Units
Geom File=g03
Flow File=f02
Flow File=f01
Plan File=p05
Plan File=p07
Y Axis Title=Elevation
X Axis Title(PF)=Main Channel Distance
X Axis Title(XS)=Station
BEGIN DESCRIPTION:
Greens Bayou Watershed
Tributary 1.95 to North Fork Greens Bayou
HCFCD Unit P145-03-00
Flood Hazard Model
10, 2, 1, 0.2% Event
Filename P145-03-00.prj
Prepared by:  Watershed Concepts  Date:
Reviewed by:                      Date:
STATUS FINAL
Appeal Revised
END DESCRIPTION:
DSS Export Rating Curves= 0
DSS Export Rating Curve Sorted= 0
DSS Export Volume Flow Curves= 0
DXF OffsetX= 0
DXF OffsetY= 0
DXF ScaleX= 1
DXF ScaleY= 10

--- P145-03-00.p07 (plan) ---

Plan Title=Floodway
Version=Version 3.0.1  Mar 2001
Short Identifier=Floodway0607
Geom File=g03
Flow File=f02
Subcritical Flow
K Sum by GR= 0
Std Step Tol= 0.01
Critical Tol= 0.01
Num of Std Step Trials= 20
Max Error Tol= 0.3
Flow Tol Ratio= 0.001
Split Flow NTrial= 30
Split Flow Tol= 0.02
Split Flow Ratio= 0.02
Log Output Level= 0
Friction Slope Method= 1
Unsteady Friction Slope Method= 2
Parabolic Critical Depth
Global Vel Dist= 0 , 0 , 0
Global Log Level= 0
CheckData=True
Encroach Param=-1 ,0,0, 2
Encroach River=P145-03-00
Encroach Reach=Reach - 1
Encroach Node=13676.7
       1    4940    5035
Encroach Node=13160.9
       1    4866    5041
Encroach Node=12325.7
       1  4963.8  5035.1
Encroach Node=11313.5
       1  4958.6  5042.2
Encroach Node=10252.9
       1  4956.1  5040.4
Encroach Node=9460.8
       1  4959.1  5041.5
Encroach Node=9369.4
       1  4959.1  5041.5
Encroach Node=9341.9
       1    4930    5060
Encroach Node=9314.4
       1  4959.1  5041.5
Encroach Node=9165.2
       1  4955.2  5037.2
Encroach Node=8777.8
       1  4955.2  5037.2
Encroach Node=7934.8
       1    4955  5034.2
Encroach Node=7858.6
       1  4966.8  5034.2
Encroach Node=7831.6
       1  4966.8  5034.2
Encroach Node=7804.6
       1  4966.8  5034.2
Encroach Node=7441.3
       1    4906  5034.2
Encroach Node=6760.2
       1 4960.25 5039.75
Encroach Node=6231.0
       1    4945    5055
Encroach Node=6215.2
       1    4945    5055
Encroach Node=6204.7
       1    4945    5055
Encroach Node=6191.2
       1    4950    5050
Encroach Node=5829.1
       1 4953.55 5046.45
Encroach Node=5180.2
       1 4952.24 5050.04
Encroach Node=5169.7
       1 4952.24 5050.04
Encroach Node=5159.2
       1 4952.24 5050.04
Encroach Node=4775.2
       1  4953.6  5055.7
Encroach Node=3887.9
       1  4950.2 5059.25
Encroach Node=3741.7
       1    4900    5065
Encroach Node=3684.2
       1    4900    5065
Encroach Node=3626.7
       1    4900    5065
Encroach Node=3234.2
       1    4954  5055.3
Encroach Node=2378.4
       1  4950.5  5054.8
Encroach Node=1398.1
       1  4957.1  5053.4
Encroach Node=423.1
       1  4954.4  5049.8
Encroach Reach=P145-03-00_0004
Encroach Node=13676.7
       1    4940    5035
Encroach Node=13160.9
       1    4866    5041
Encroach Node=12325.7
       1  4963.8  5035.1
Encroach Node=11313.5
       1  4958.6  5042.2
Encroach Node=10252.9
       1  4956.1  5040.4
Encroach Node=9460.8
       1  4959.1  5041.5
Encroach Node=9369.4
       1  4959.1  5041.5
Encroach Node=9341.9
       1    4930    5060
Encroach Node=9314.4
       1  4959.1  5041.5
Encroach Node=9165.2
       1  4955.2  5037.2
Encroach Node=8777.8
       1  4955.2  5037.2
Encroach Node=7934.8
       1    4955  5034.2
Encroach Node=7858.6
       1  4966.8  5034.2
Encroach Node=7831.6
       1  4966.8  5034.2
Encroach Node=7804.6
       1  4966.8  5034.2
Encroach Node=7441.3
       1    4906  5034.2
Encroach Node=6760.2
       1 4960.25 5039.75
Encroach Node=6231.0
       1    4945    5055
Encroach Node=6215.2
       1    4945    5055
Encroach Node=6204.7
       1    4945    5055
Encroach Node=6191.2
       1    4950    5050
Encroach Node=5829.1
       1 4953.55 5046.45
Encroach Node=5180.2
       1 4952.24 5050.04
Encroach Node=5169.7
       1 4952.24 5050.04
Encroach Node=5159.2
       1 4952.24 5050.04
Encroach Node=4775.2
       1  4953.6  5055.7
Encroach Node=3887.9
       1  4950.2 5059.25
Encroach Node=3741.7
       1    4900    5065
Encroach Node=3684.2
       1    4900    5065
Encroach Node=3626.7
       1    4900    5065
Encroach Node=3234.2
       1    4954  5055.3
Encroach Node=2378.4
       1  4950.5  5054.8
Encroach Node=1398.1
       1  4957.1  5053.4
Encroach Node=423.1
       1  4954.4  5049.8
Computation Interval=1HOUR
Output Interval=1HOUR
Run HTab= 0
Run UNet= 0
Run PostProcess= 0
UNET Theta= 1
UNET ZTol= 0.02
UNET ZSATol= 0.1
UNET MxIter= 20
UNET MaxInSteps= 20
UNET DtIC= 0
UNET DtMin= 0
UNET MaxCRTS= 20
UNET WFStab= 2
UNET SFStab= 1
UNET WFX= 1
UNET SFX= 1
UNET Convert EG Bridges=-1
UNET Use Existing IB Tables=-1
Instantaneous Interval=1HOUR
Write IC File= 0
Write Velocity= 0
Write Detailed= 0

--- P145-03-00.p05 (plan) ---

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Plan Title=FEMA Effective June 2007
Short Identifier=FEMAeff0607
Geom File=g03
Flow File=f01

--- P145-03-00.f02 (steady flow) ---

Flow Title=Floodway
Version=Version 3.0.1  Mar 2001
Number of Profiles= 2
Profile Names=1PCT_100yr, 1PCTFloodway_100yrFW
River Rch & RM=P145-03-00,P145-03-00_0004      ,13676.7
     264     264
River Rch & RM=P145-03-00,P145-03-00_0004      ,12325.7
     307     307
River Rch & RM=P145-03-00,P145-03-00_0004      ,11313.5
     359     359
River Rch & RM=P145-03-00,P145-03-00_0004      ,10252.9
    1096    1096
River Rch & RM=P145-03-00,P145-03-00_0004      ,9460.8
    1121    1121
River Rch & RM=P145-03-00,P145-03-00_0004      ,9369.4
    1147    1147
River Rch & RM=P145-03-00,P145-03-00_0004      ,9165.2
    1217    1217
River Rch & RM=P145-03-00,P145-03-00_0004      ,8777.8
    1383    1383
River Rch & RM=P145-03-00,P145-03-00_0004      ,7934.8
    1411    1411
River Rch & RM=P145-03-00,P145-03-00_0004      ,7858.6
    1491    1491
River Rch & RM=P145-03-00,P145-03-00_0004      ,7441.3
    1654    1654
River Rch & RM=P145-03-00,P145-03-00_0004      ,6760.2
    1793    1793
River Rch & RM=P145-03-00,P145-03-00_0004      ,6231
    1804    1804
River Rch & RM=P145-03-00,P145-03-00_0004      ,6215.2
    1906    1906
River Rch & RM=P145-03-00,P145-03-00_0004      ,5829.1
    2104    2104
River Rch & RM=P145-03-00,P145-03-00_0004      ,5180.2
    2238    2238
River Rch & RM=P145-03-00,P145-03-00_0004      ,4775.2
    2562    2562
River Rch & RM=P145-03-00,P145-03-00_0004      ,3887.9
    2619    2619
River Rch & RM=P145-03-00,P145-03-00_0004      ,3741.7
    2682    2682
River Rch & RM=P145-03-00,P145-03-00_0004      ,3234.2
    2792    2792
River Rch & RM=P145-03-00,P145-03-00_0004      ,2378.4
    2923    2923
River Rch & RM=P145-03-00,P145-03-00_0004      ,1398.1
    3059    3059
Boundary for River Rch & Prof#=P145-03-00,P145-03-00_0004      , 1
Up Type= 0
Dn Type= 3
Dn Slope=.0013
Boundary for River Rch & Prof#=P145-03-00,P145-03-00_0004      , 2
Up Type= 0
Dn Type= 3
Dn Slope=.0013
DSS Import GetInterval= 0
DSS Import GetPeak= 0
DSS Import FillOption= 0

--- P145-03-00.f01 (steady flow) ---

Flow Title=FEMA Effective June 2007
Version=Version 3.0.1  Mar 2001
Number of Profiles= 4
Profile Names=10PCT_10yr, 2PCT_50yr, 1PCT_100yr, 0.2PCT_500yr
River Rch & RM=P145-03-00,P145-03-00_0004      ,13676.7
     150     225     264     377
River Rch & RM=P145-03-00,P145-03-00_0004      ,12325.7
     174     262     307     439
River Rch & RM=P145-03-00,P145-03-00_0004      ,11313.5
     204     307     359     514
River Rch & RM=P145-03-00,P145-03-00_0004      ,10252.9
     622     936    1096    1567
River Rch & RM=P145-03-00,P145-03-00_0004      ,9460.8
     636     957    1121    1602
River Rch & RM=P145-03-00,P145-03-00_0004      ,9369.4
     651     979    1147    1638
River Rch & RM=P145-03-00,P145-03-00_0004      ,9165.2
     691    1039    1217    1737
River Rch & RM=P145-03-00,P145-03-00_0004      ,8777.8
     787    1181    1383    1972
River Rch & RM=P145-03-00,P145-03-00_0004      ,7934.8
     803    1205    1411    2011
River Rch & RM=P145-03-00,P145-03-00_0004      ,7858.6
     849    1274    1491    2124
River Rch & RM=P145-03-00,P145-03-00_0004      ,7441.3
     942    1413    1654    2354
River Rch & RM=P145-03-00,P145-03-00_0004      ,6760.2
    1022    1532    1793    2550
River Rch & RM=P145-03-00,P145-03-00_0004      ,6231
    1028    1541    1804    2565
River Rch & RM=P145-03-00,P145-03-00_0004      ,6215.2
    1087    1629    1906    2709
River Rch & RM=P145-03-00,P145-03-00_0004      ,5829.1
    1201    1798    2104    2987
River Rch & RM=P145-03-00,P145-03-00_0004      ,5180.2
    1278    1912    2238    3175
River Rch & RM=P145-03-00,P145-03-00_0004      ,4775.2
    1465    2190    2562    3630
River Rch & RM=P145-03-00,P145-03-00_0004      ,3887.9
    1498    2239    2619    3711
River Rch & RM=P145-03-00,P145-03-00_0004      ,3741.7
    1540    2301    2682    3787
River Rch & RM=P145-03-00,P145-03-00_0004      ,3234.2
    1612    2408    2792    3920
River Rch & RM=P145-03-00,P145-03-00_0004      ,2378.4
    1700    2538    2923    4077
River Rch & RM=P145-03-00,P145-03-00_0004      ,1398.1
    1791    2674    3059    4240
Boundary for River Rch & Prof#=P145-03-00,P145-03-00_0004      , 1
Up Type= 0
Dn Type= 3
Dn Slope=.0013
Boundary for River Rch & Prof#=P145-03-00,P145-03-00_0004      , 2
Up Type= 0
Dn Type= 3
Dn Slope=.0013
Boundary for River Rch & Prof#=P145-03-00,P145-03-00_0004      , 3
Up Type= 0
Dn Type= 3
Dn Slope=.0013
Boundary for River Rch & Prof#=P145-03-00,P145-03-00_0004      , 4
Up Type= 0
Dn Type= 3
Dn Slope=.0013
DSS Import GetInterval= 0
DSS Import GetPeak= 0
DSS Import FillOption= 0

--- P145-03-00.g03 (geometry) ---

Geom Title=P145-03-00 June 2007
Version=Version 3.0.1  Mar 2001

River Reach=P145-03-00      ,P145-03-00_0004
Reach XY= 30
      3091222.28     13930948.49       3091941.5       13929866.
       3093106.5       13928175.      3093754.75       13927222.
      3094259.57       13926534.      3094386.25       13926305.
      3094551.95     13926062.46      3094640.55     13925888.13
      3094762.01     13925452.15       3095069.5       13924124.
      3095209.74     13923549.79      3095256.34     13923328.96
      3095297.25       13923101.       3095363.5       13922848.
      3095446.75       13922674.        3095533.       13922514.
      3095591.25       13922360.      3095585.75       13922297.
        3095538.       13922224.      3095447.25       13922147.
        3095399.       13922045.      3095381.25       13921818.
       3095354.5       13921594.      3095299.75       13921054.
      3095240.13     13920514.92      3095227.97     13920425.78
        3095230.     13920340.69      3095240.13     13920198.88
      3095275.46     13919203.31       3095292.8     13918853.65

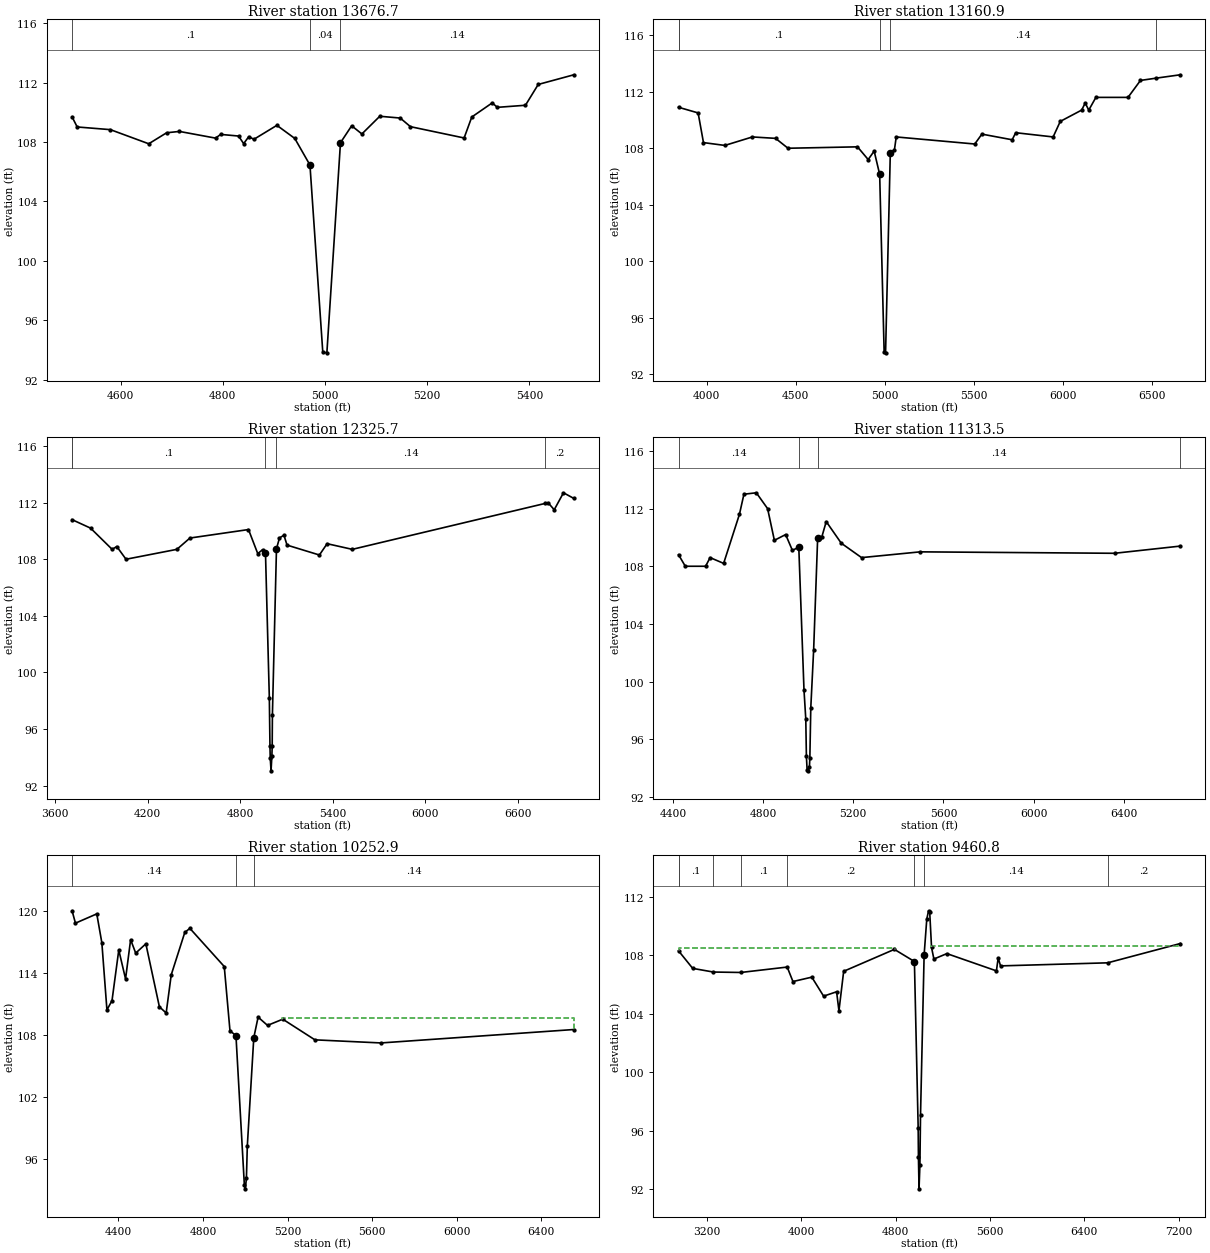
Type RM Length L Ch R = 1 ,13676.7 ,515.8,515.8,515.8
BEGIN DESCRIPTION:
Cross Section 13676.7 - Interpolated
END DESCRIPTION:
XS GIS Cut Line= 4
      3091642.85     13931209.14      3091420.33      13931073.3
      3091203.47     13930936.64      3090817.27     13930678.18
#Sta/Elev= 30
  4505.2  109.69  4515.2  109.01  4580.2  108.83  4655.2  107.88  4690.2  108.62
  4715.2  108.71  4785.9  108.26  4795.9  108.51  4830.9   108.4  4840.9  107.89
  4850.9  108.36  4860.9  108.18  4905.9  109.12  4940.9  108.24  4970.6  106.45
  4995.7   93.87  5003.7   93.82  5030.3  107.95  5052.2  109.09  5072.2  108.54
  5107.2  109.73  5147.2  109.61  5167.2  109.03  5272.2  108.27  5287.2  109.68
  5327.2  110.63  5337.2  110.33  5392.2  110.47  5417.2  111.87  5486.9  112.52
#Mann= 3 , 1 , 0
  4505.2      .1       0  4970.6     .04       0  5030.3     .14       0
Bank Sta=4970.6,5030.3
XS Rating Curve= 0
Exp/Cntr=.3,.1

Type RM Length L Ch R = 1 ,13160.9 ,834.4,835.2,833.6
BEGIN DESCRIPTION:
Cross Section 13160.9
END DESCRIPTION:
XS GIS Cut Line= 6
       3092388.6     13931252.01      3092124.53     13930932.35
      3091589.46      13930557.1      3091513.02     13930522.36
      3090422.02     13929813.55      3090060.67     13929771.86
#Sta/Elev= 30
  3841.5   110.9  3951.5   110.5  3981.5   108.4  4101.5   108.2  4256.1   108.8
  4386.1   108.7  4456.1     108  4846.1   108.1  4906.1   107.2  4939.7   107.8
  4970.6  106.15  4995.7   93.57  5003.7   93.52  5030.3  107.65  5053.6   107.9
  5063.6   108.8  5504.4   108.3  5544.4     109  5714.4   108.6  5734.4   109.1
  5944.4   108.8  5984.4   109.9  6104.4   110.7  6124.4   111.2  6144.4   110.7
  6184.4   111.6  6364.7   111.6  6434.7   112.8  6521.8  112.96  6658.4   113.2
#Mann= 5 , 1 , 0
  3841.5      .2       0  3841.5      .1       0  4970.6     .04       0
  5030.3     .14       0  6521.8      .2       0
Bank Sta=4970.6,5030.3
XS Rating Curve= 0
Exp/Cntr=.3,.1

Type RM Length L Ch R = 1 ,12325.7 ,1009.9,1012.2,1014.8
BEGIN DESCRIPTION:
Cross Section 12325.7
END DESCRIPTION:
XS GIS Cut Line= 5
      3093215.61     13930932.29      3092954.44     13930639.27
      3092427.84     13930084.95      3091513.22     13929562.31
      3090075.95     13929546.47
#Sta/Elev= 30
    3709   110.8    3829   110.2    3969   108.7    3999   108.9    4059     108
    4389   108.7  4473.6   109.5  4853.6   110.1  4913.6   108.4  4944.5  108.67
  4963.8  108.45  4988.8   98.18  4992.8   94.78  4994.6   93.96  4999.9   93.04
  5005.3    94.1  5007.3   94.77  5008.7   96.99  5035.1  108.74  5054.6  109.51
  5083.6   109.7  5103.6     109  5313.6   108.3  5363.6   109.1    5527   108.7
  6779.2  111.95    6797     112    6837   111.5    6897   112.7  6964.4   112.3
#Mann= 5 , 1 , 0
    3709      .2       0    3709      .1       0  4963.8     .04       0
  5035.1     .14       0  6779.2      .2       0
Bank Sta=4963.8,5035.1
XS Rating Curve= 0
Exp/Cntr=.3,.1

Type RM Length L Ch R = 1 ,11313.5 ,1065.3,1060.6,1059.1
BEGIN DESCRIPTION:
Cross Section 11313.5
END DESCRIPTION:
XS GIS Cut Line= 6
      3094813.99     13930420.39      3094120.84     13929675.81
      3093686.33     13929448.29      3092736.67     13929118.85
      3091810.17      13928548.7      3091018.29      13928548.7
#Sta/Elev= 30
  4425.3   108.8  4455.3     108  4545.3     108  4565.3   108.6  4625.3   108.2
  4695.3   111.6  4715.3     113  4770.3   113.1  4820.3     112  4850.3   109.8
  4900.3   110.2  4930.3   109.1  4958.6  109.33  4981.7    99.4  4989.6    97.4
  4992.3   94.83  4995.4   93.88  4999.3    93.8  5005.8   94.06  5007.7   94.72
  5011.8   98.17  5024.5  102.21  5042.2  109.94  5060.8  110.04  5080.3   111.1
    5147   109.6    5237   108.6    5497     109  6358.7   108.9  6650.6   109.4
#Mann= 4 , 1 , 0
  4425.3     .14       0  4958.6     .04       0  5042.2     .14       0
  6650.6      .2       0
Bank Sta=4958.6,5042.2
XS Rating Curve= 0
Exp/Cntr=.3,.1

Type RM Length L Ch R = 1 ,10252.9 ,802.3,792.1,785.4
BEGIN DESCRIPTION:
Cross Section 10252.9
END DESCRIPTION:
XS GIS Cut Line= 6
       3095191.6     13930265.27      3094410.52      13928951.9
      3093832.91     13928562.17      3093318.71     13928224.02
      3093077.18     13928073.57      3091769.71     13927397.29
#Sta/Elev= 30
  4181.4     120  4197.4   118.8  4298.2   119.7  4322.2   116.9  4346.2   110.4
  4370.2   111.3  4402.2   116.2  4434.2   113.4  4458.2   117.2  4482.2   115.9
  4530.2   116.8  4594.2   110.7  4626.2   110.1  4650.2   113.8  4714.2   117.9
  4738.2   118.3  4900.8   114.6  4927.9  108.37  4956.1  107.92  4995.7   93.49
  5000.6   93.07  5005.6   94.12  5009.8   97.22  5040.4  107.71  5060.8   109.7
  5105.4   108.9  5177.4   109.5  5329.4   107.5  5641.4   107.2  6553.4   108.5
#Mann= 3 , 1 , 0
  4181.4     .14       0  4956.1     .04       0  5040.4     .14       0
#XS Ineff= 2 , 0
       0  4738.2   118.3  5171.4       0   109.6
Permanent Ineff=
       F       F
Bank Sta=4956.1,5040.4
XS Rating Curve= 0
Exp/Cntr=.3,.1

Type RM Length L Ch R = 1 ,9460.8  ,88,91.4,97.3
BEGIN DESCRIPTION:
Cross Section 9460.8-Interpolated
END DESCRIPTION:
XS GIS Cut Line= 6
      3095541.05     13928619.18      3095393.67     13928418.72
      3093678.82      13927501.8      3093496.84     13927417.81
      3092253.08     13926782.84      3091551.94     13926654.78
#Sta/Elev= 30
  2959.4   108.3  3079.4   107.1  3254.4  106.85  3486.7  106.82  3880.7  107.19
  3929.4   106.2  4089.4   106.5  4189.4   105.2  4299.4   105.5  4319.4   104.2
  4359.4   106.9  4789.4   108.4  4959.1  107.57    4991   96.21  4993.2   94.22
  4998.4   92.02  5005.8   93.67  5010.9   97.04  5041.5  108.02    5064  110.47
    5079  111.04    5089  110.93  5104.4  108.53  5124.4  107.74  5234.4  108.11
  5654.4  106.93  5669.4  107.81  5689.4  107.27  6597.6  107.48  7213.6   108.8
#Mann= 8 , 1 , 0
  2959.4      .2       0  2959.4      .1       0  3254.4     .14       0
  3486.7      .1       0  3880.7      .2       0  4959.1     .04       0
  5041.5     .14       0  6597.6      .2       0
#XS Ineff= 2 , 0
       0  4795.4   108.5    5104       0   108.6
Permanent Ineff=
       F       F
Bank Sta=4959.1,5041.5
XS Rating Curve= 0
Exp/Cntr=.5,.3

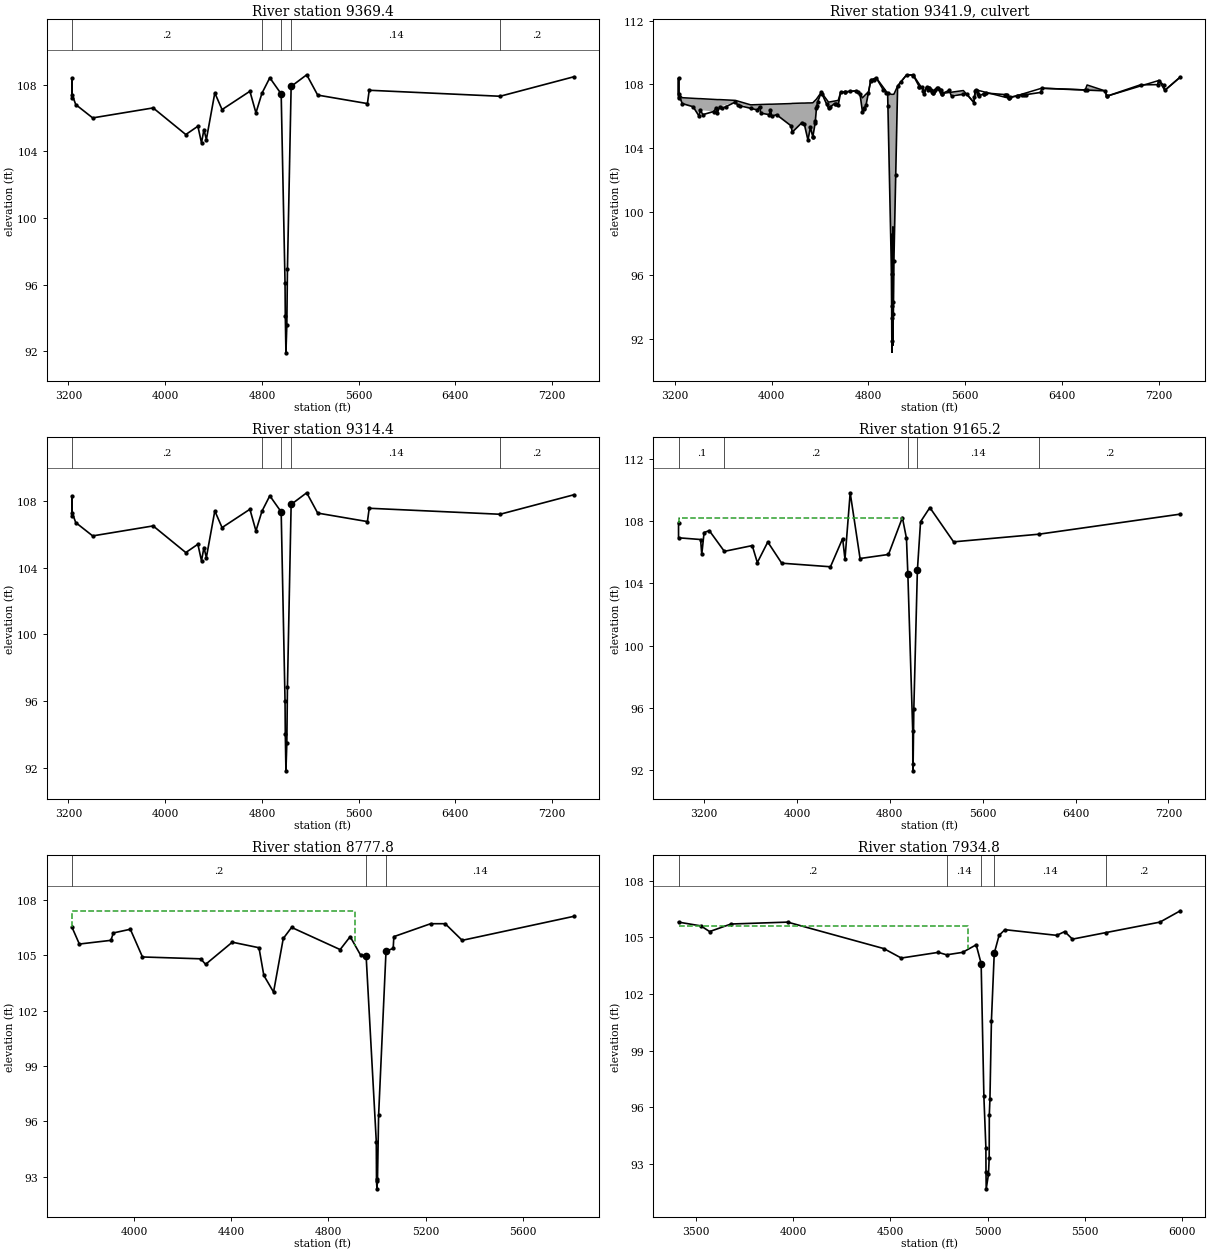
Type RM Length L Ch R = 1 ,9369.4  ,55,55,55
BEGIN DESCRIPTION:
Upstream Section of Bridge/Culvert/Weir
END DESCRIPTION:
XS GIS Cut Line= 6
      3095594.84     13928438.06      3094177.02     13927704.66
      3093468.19     13927278.53      3093391.42     13927228.47
      3093089.86     13926881.84        3091509.     13926515.33
#Sta/Elev= 30
    3230  107.19  3230.3  108.41  3230.4  107.41  3260.4  106.81  3400.4  106.01
  3900.4  106.61  4170.4  105.01  4270.3  105.51  4300.3  104.51  4320.3  105.31
  4340.4  104.71  4410.3  107.51  4470.3  106.51  4700.5  107.61  4750.5  106.31
    4800  107.49  4865.1  108.42  4959.1  107.45    4991   96.09  4993.2    94.1
  4998.4    91.9  5005.8   93.55  5010.9   96.92  5041.5   107.9  5170.2   108.6
    5261  107.38  5672.2  106.87  5687.2  107.67  6769.1  107.31  7379.3  108.48
#Mann= 5 ,-1 , 0
    3230      .2       0    4800     .14       0  4959.1     .04       0
  5041.5     .14       0  6769.1      .2       0
#XS Ineff= 2 , 0
       0 4951.34   106.9 5050.65       0  106.93
Permanent Ineff=
       F       F
Bank Sta=4959.1,5041.5
XS Rating Curve= 0
Exp/Cntr=.5,.3

Type RM Length L Ch R = 2 ,9341.9  ,,,
BEGIN DESCRIPTION:
HARRELL DWYER ROAD
Structure ID: P43-05
END DESCRIPTION:
Bridge Culvert--1,0,-1,-1, 0
Deck Dist Width WeirC Skew NumUp NumDn MinLoCord MaxHiCord MaxSubmerge Is_Ogee
10,35,3,0, 60, 60, , , .95, 0, 1,1,,
    3230  3230.3  3230.4  3260.4  3350.4  3400.4  3410.4  3550.4  3570.4  3700.4
  3826.6  3980.4  3990.4  4000.4  4160.4  4170.4  4250.3  4270.3  4300.3  4320.3
  4340.4  4370.3  4410.3  4470.3  4550.3  4570.3  4700.5  4730.5  4750.5  4780.5
    4800  4820.4  4865.1  4959.1    4991  4993.2  4995.8  4998.4  5005.8  5010.9
  5041.5  5115.9  5170.2    5261    5281  5332.2  5367.2  5407.2  5585.3  5672.2
  5687.2  5959.7  6234.7  6592.9  6608.3  6755.9  6770.9  7200.9  7250.9  7379.3
  107.18  108.41  107.41  107.17  107.13  107.11  107.11  107.05  107.05     107
  106.72  106.76  106.76  106.76   106.8  106.81  106.83  106.83  106.84  106.84
  106.85  107.08  107.51  106.89     107  107.51  107.61  107.41  107.16   107.4
  107.49   108.3  108.42  107.45  107.38  107.38  107.38  107.38  107.38  107.39
   107.9  108.61   108.6  107.56  107.84  107.47  107.79  107.43  107.62  106.87
  107.67  107.14  107.77  107.66  107.97   107.6  107.26  108.25  107.63  108.47
  107.18   108.4   107.4   106.8   106.6     106   106.4   106.2   106.6   106.9
   106.5   106.1   106.4     106   105.4     105   105.6   105.5   104.5   105.3
   104.7   106.5   107.5   106.5   106.7   107.5   107.6   107.4   106.3   106.7
  107.48  108.29  108.41  107.44   96.08   94.09    93.3   91.89   93.54   96.91
  107.89   108.6  108.59  107.37  107.83  107.46  107.78  107.42  107.38  106.86
  107.66  107.13  107.76  107.65  107.65   107.6  107.26  108.25  107.63  108.47
    3230  3230.3  3230.4  3260.4  3350.4  3400.4  3410.4  3550.4  3570.4  3700.4
  3826.6  3980.4  3990.4  4000.4  4160.4  4170.4  4250.3  4270.3  4300.3  4320.3
  4340.4  4370.3  4410.3  4470.3  4550.3  4570.3  4700.5  4730.5  4750.5  4780.5
    4800  4820.4  4865.1  4959.1    4991  4993.2  4995.8  4998.4  5005.8  5010.9
  5041.5  5115.9  5170.2    5261    5281  5332.2  5367.2  5407.2  5585.3  5672.2
  5687.2  5959.7  6234.7  6592.9  6608.3  6755.9  6770.9  7200.9  7250.9  7379.3
  107.18  108.41  107.41  107.17  107.13  107.11  107.11  107.05  107.05     107
  106.72  106.76  106.76  106.76   106.8  106.81  106.83  106.83  106.84  106.84
  106.85  107.08  107.51  106.89     107  107.51  107.61  107.41  107.16   107.4
  107.49   108.3  108.42  107.45  107.38  107.38  107.38  107.38  107.38  107.39
   107.9  108.61   108.6  107.56  107.84  107.47  107.79  107.43  107.62  106.87
  107.67  107.14  107.77  107.66  107.97   107.6  107.26  108.25  107.63  108.47
  107.09  108.31  107.31  106.71  106.51  105.91  106.31  106.11  106.51  106.81
  106.41  106.01  106.31  105.91  105.31  104.91  105.51  105.41  104.41  105.21
  104.61  106.41  107.41  106.41  106.61  107.41  107.51  107.31  106.21  106.61
  107.39   108.2  108.32  107.35   95.99      94   93.21    91.8   93.45   96.82
   107.8  108.51   108.5  107.28  107.74  107.37  107.69  107.33  107.29  106.77
  107.57  107.04  107.67  107.56  107.56  107.51  107.17  108.16  107.54  108.38
BR Coef= 1 , 0 , 0 ,1.25, 0 ,,,.8,-1,2,0,
WSPro=,,,, 1 ,,,, 0 ,,,, 0 ,,,,-1 ,-1 ,-1 , 0 , 0 , 0 , 0 , 0
Culvert=1,7.5,,35,.015,.5,1,1,3,91.12,4994.9,90.66,4994.9,Culvert #1  , 0 ,10
Culvert Bottom n=.015
Culvert=1,7.5,,35,.015,.5,1,1,3,91.57,5003.2,90.53,5003.2,Culvert #2  , 0 ,10
Culvert Bottom n=.015
BR U #Sta/Elev= 139
    3230  107.18  3230.3   108.4  3230.4   107.4  3260.4   106.8  3350.4   106.6
  3400.4     106  3410.4   106.4  3430.4   106.1  3520.4   106.3  3540.4   106.5
  3550.4   106.2  3570.4   106.6  3590.4   106.5  3620.4   106.6  3700.4   106.9
  3720.4   106.7  3739.8  106.66  3826.6   106.5  3880.4   106.4  3900.4   106.6
  3910.4   106.2  3980.4   106.1  3990.4   106.4  4000.4     106  4040.4   106.1
  4160.4   105.4  4170.4     105  4250.3   105.6  4270.3   105.5  4300.3   104.5
  4320.3   105.3  4340.3   104.7  4340.4   104.7  4360.3   105.6  4361.3  105.69
  4370.3   106.5  4373.9  106.64  4380.3   106.9  4410.3   107.5  4417.8  107.38
    4455  106.76  4470.3   106.5  4483.4  106.58  4520.3   106.8  4535.3  106.75
  4550.3   106.7  4570.3   107.5  4603.7  107.53  4605.2  107.53  4647.5  107.56
  4700.5   107.6  4713.1  107.52  4730.5   107.4  4750.5   106.3  4762.4  106.46
  4765.9  106.51  4780.5   106.7    4800  107.48  4820.4  108.29  4821.2  108.21
  4843.8  108.31  4865.1  108.41    4923  107.66  4948.6  107.46  4959.1  107.44
  4961.4  106.62    4991   96.08  4993.2   94.09  4995.8    93.3  4998.4   91.89
  5005.8   93.54  5006.8    94.3  5010.9   96.91  5025.9  102.29  5041.5  107.89
    5068  108.16  5115.9   108.6  5170.2  108.59  5172.1  108.56  5220.8  107.86
    5221  107.86    5246  107.82    5251  107.56    5261  107.37    5281  107.83
    5291  107.66  5302.2  107.78  5303.1  107.77  5314.4  107.65  5323.5  107.55
  5332.2  107.46  5334.1  107.48  5344.7  107.57  5354.1  107.66  5367.2  107.78
    5374  107.76  5393.9  107.68  5397.2  107.67  5402.5  107.54  5407.2  107.42
  5408.5  107.42  5467.2  107.63  5487.2  107.28  5585.3  107.38  5612.2  107.41
  5672.2  106.86  5676.8  107.19  5682.2  107.57  5687.2  107.66  5695.6  107.56
  5706.2  107.43  5717.2   107.3  5751.8  107.41  5756.3  107.42  5769.7  107.46
  5933.1  107.36  5936.7  107.36  5949.7  107.35  5959.7  107.13  5961.9  107.14
  5974.7  107.21    6025  107.27  6037.6  107.28  6071.2  107.32  6086.5  107.34
  6100.7  107.36  6224.7   107.5  6234.7  107.76  6592.9  107.65  6608.3  107.65
  6755.9   107.6  6769.1   107.3  6770.9  107.26  7050.9  107.98  7190.9  107.99
  7200.9  108.25  7240.9  107.96  7250.9  107.63  7379.3  108.47
BR U #Mann= 5
    3230      .2    4800     .14  4959.1     .04  5041.5     .14  6769.1      .2
BR U Banks=4959.1,5041.5
BR D #Sta/Elev= 139
    3230  107.09  3230.3  108.31  3230.4  107.31  3260.4  106.71  3350.4  106.51
  3400.4  105.91  3410.4  106.31  3430.4  106.01  3520.4  106.21  3540.4  106.41
  3550.4  106.11  3570.4  106.51  3590.4  106.41  3620.4  106.51  3700.4  106.81
  3720.4  106.61  3739.8  106.57  3826.6  106.41  3880.4  106.31  3900.4  106.51
  3910.4  106.11  3980.4  106.01  3990.4  106.31  4000.4  105.91  4040.4  106.01
  4160.4  105.31  4170.4  104.91  4250.3  105.51  4270.3  105.41  4300.3  104.41
  4320.3  105.21  4340.3  104.61  4340.4  104.61  4360.3  105.51  4361.3   105.6
  4370.3  106.41  4373.9  106.55  4380.3  106.81  4410.3  107.41  4417.8  107.29
    4455  106.67  4470.3  106.41  4483.4  106.49  4520.3  106.71  4535.3  106.66
  4550.3  106.61  4570.3  107.41  4603.7  107.44  4605.2  107.44  4647.5  107.47
  4700.5  107.51  4713.1  107.43  4730.5  107.31  4750.5  106.21  4762.4  106.37
  4765.9  106.42  4780.5  106.61    4800  107.39  4820.4   108.2  4821.2  108.12
  4843.8  108.22  4865.1  108.32    4923  107.57  4948.6  107.37  4959.1  107.35
  4961.4  106.53    4991   95.99  4993.2      94  4995.8   93.21  4998.4    91.8
  5005.8   93.45  5006.8   94.21  5010.9   96.82  5025.9   102.2  5041.5   107.8
    5068  108.07  5115.9  108.51  5170.2   108.5  5172.1  108.47  5220.8  107.77
    5221  107.77    5246  107.73    5251  107.47    5261  107.28    5281  107.74
    5291  107.57  5302.2  107.69  5303.1  107.68  5314.4  107.56  5323.5  107.46
  5332.2  107.37  5334.1  107.39  5344.7  107.48  5354.1  107.57  5367.2  107.69
    5374  107.67  5393.9  107.59  5397.2  107.58  5402.5  107.45  5407.2  107.33
  5408.5  107.33  5467.2  107.54  5487.2  107.19  5585.3  107.29  5612.2  107.32
  5672.2  106.77  5676.8   107.1  5682.2  107.48  5687.2  107.57  5695.6  107.47
  5706.2  107.34  5717.2  107.21  5751.8  107.32  5756.3  107.33  5769.7  107.37
  5933.1  107.27  5936.7  107.27  5949.7  107.26  5959.7  107.04  5961.9  107.05
  5974.7  107.12    6025  107.18  6037.6  107.19  6071.2  107.23  6086.5  107.25
  6100.7  107.27  6224.7  107.41  6234.7  107.67  6592.9  107.56  6608.3  107.56
  6755.9  107.51  6769.1  107.21  6770.9  107.17  7050.9  107.89  7190.9   107.9
  7200.9  108.16  7240.9  107.87  7250.9  107.54  7379.3  108.38
BR D #Mann= 5
    3230      .2    4800     .14  4959.1     .04  5041.5     .14  6769.1      .2
BR D Banks=4959.1,5041.5
BC Design=,, 0 ,, 0 ,,,,,,
BC HTab HWMax=108.61

Type RM Length L Ch R = 1 ,9314.4  ,149.2,149.2,149.2
BEGIN DESCRIPTION:
Downstream Section of Bridge/Culvert/Weir
END DESCRIPTION:
XS GIS Cut Line= 6
      3095621.33     13928390.12      3094207.92     13927659.16
      3093499.09     13927233.03      3093422.32     13927182.97
      3093120.76     13926836.34      3091539.89     13926469.82
#Sta/Elev= 30
    3230   107.1  3230.3  108.32  3230.4  107.32  3260.4  106.72  3400.4  105.92
  3900.4  106.52  4170.4  104.92  4270.3  105.42  4300.3  104.42  4320.3  105.22
  4340.4  104.62  4410.3  107.42  4470.3  106.42  4700.5  107.52  4750.5  106.22
    4800   107.4  4865.1  108.33  4959.1  107.36    4991      96  4993.2   94.01
  4998.4   91.81  5005.8   93.46  5010.9   96.83  5041.5  107.81  5170.2  108.51
    5261  107.29  5672.2  106.78  5687.2  107.58  6769.1  107.22  7379.3  108.39
#Mann= 5 ,-1 , 0
    3230      .2       0    4800     .14       0  4959.1     .04       0
  5041.5     .14       0  6769.1      .2       0
#XS Ineff= 2 , 0
       0 4951.34   106.9 5050.65       0  106.93
Permanent Ineff=
       F       F
Bank Sta=4959.1,5041.5
XS Rating Curve= 0
Exp/Cntr=.5,.3

Type RM Length L Ch R = 1 ,9165.2  ,395.4,387.4,384.3
BEGIN DESCRIPTION:
Cross Section 9165.2-Interpolated
END DESCRIPTION:
XS GIS Cut Line= 6
       3095494.6     13928250.11      3093903.55     13927299.35
      3093544.33     13927099.49      3093159.98      13926832.7
      3092258.05     13926643.77      3091662.12     13926339.53
#Sta/Elev= 30
  2979.5   107.9  2979.6  106.92  3169.6  106.81  3179.6  105.85  3199.6  107.26
  3244.6  107.38  3374.2  106.05  3614.6  106.42  3658.4  105.33  3748.4  106.65
  3868.4  105.29  4288.4  105.06  4393.4  106.87  4413.4  105.55  4458.4  109.81
  4543.4  105.59  4788.4  105.85  4908.1  108.22  4943.1  106.89  4955.2  104.58
  4997.1   94.52    4998    92.4  4999.8   91.96  5006.7   95.95  5037.2  104.83
  5064.6  107.95  5144.6  108.86  5349.2  106.66  6083.1  107.15  7302.6  108.44
#Mann= 5 , 1 , 0
  2979.5      .1       0  3374.2      .2       0  4955.2     .04       0
  5037.2     .14       0  6083.1      .2       0
#XS Ineff= 2 , 0
       0  4901.1   108.2               0
Permanent Ineff=
       F       F
Bank Sta=4955.2,5037.2
XS Rating Curve= 0
Exp/Cntr=.3,.1

Type RM Length L Ch R = 1 ,8777.8  ,875.9,843,833
BEGIN DESCRIPTION:
Cross Section 8777.8
END DESCRIPTION:
XS GIS Cut Line= 5
      3094957.56     13927702.26      3094254.04     13927134.06
      3094077.74     13926969.32       3093807.7     13926776.91
      3093276.42     13926520.51
#Sta/Elev= 30
  3743.9   106.5  3773.9   105.6  3903.9   105.8  3913.9   106.2  3983.9   106.4
  4033.9   104.9  4273.9   104.8  4293.9   104.5  4403.9   105.7  4513.9   105.4
  4533.9   103.9  4573.9     103  4613.9   105.9  4648.2   106.5  4848.2   105.3
  4889.5     106  4932.1  105.01  4955.2  104.97  4997.1   94.91    4998   92.79
  4999.8   92.35  5002.1   92.86  5006.7   96.34  5037.2  105.22  5066.7  105.36
  5069.5     106    5221   106.7    5281   106.7    5351   105.8    5811   107.1
#Mann= 3 , 1 , 0
  3743.9      .2       0  4955.2     .04       0  5037.2     .14       0
#XS Ineff= 2 , 0
       0  4910.2   107.4               0
Permanent Ineff=
       F       F
Bank Sta=4955.2,5037.2
XS Rating Curve= 0
Exp/Cntr=.3,.1

Type RM Length L Ch R = 1 ,7934.8  ,73.2,76.2,80
BEGIN DESCRIPTION:
Cross Section 7934.8-Interpolated
END DESCRIPTION:
XS GIS Cut Line= 6
      3095978.62     13926611.13      3095447.92     13926428.95
       3094828.7     13926361.67      3094684.67     13926311.85
        3094097.     13926033.68      3093503.13     13926069.35
#Sta/Elev= 30
  3409.9   105.8  3524.9   105.6  3569.9   105.3  3679.9   105.7    3971   105.8
    4466   104.4    4556   103.9  4746.3   104.2  4789.1  104.07  4871.3   104.2
  4941.3   104.6  4966.8  103.61  4980.9   96.58  4991.2   93.87  4991.8   92.56
  4992.9   91.69  5004.5   92.46  5008.2   93.32  5008.8   95.59  5012.1   96.45
  5019.7  100.58  5034.2  104.15  5059.1   105.1  5089.1   105.4  5355.9   105.1
  5396.6   105.3  5436.6   104.9  5610.8  105.25  5886.6   105.8  5991.6   106.4
#Mann= 5 , 1 , 0
  3409.9      .2       0  4789.1     .14       0  4966.8     .04       0
  5034.2     .14       0  5610.8      .2       0
#XS Ineff= 2 , 0
       0  4901.3   105.6               0
Permanent Ineff=
       F       F
Bank Sta=4966.8,5034.2
XS Rating Curve= 0
Exp/Cntr=.5,.3

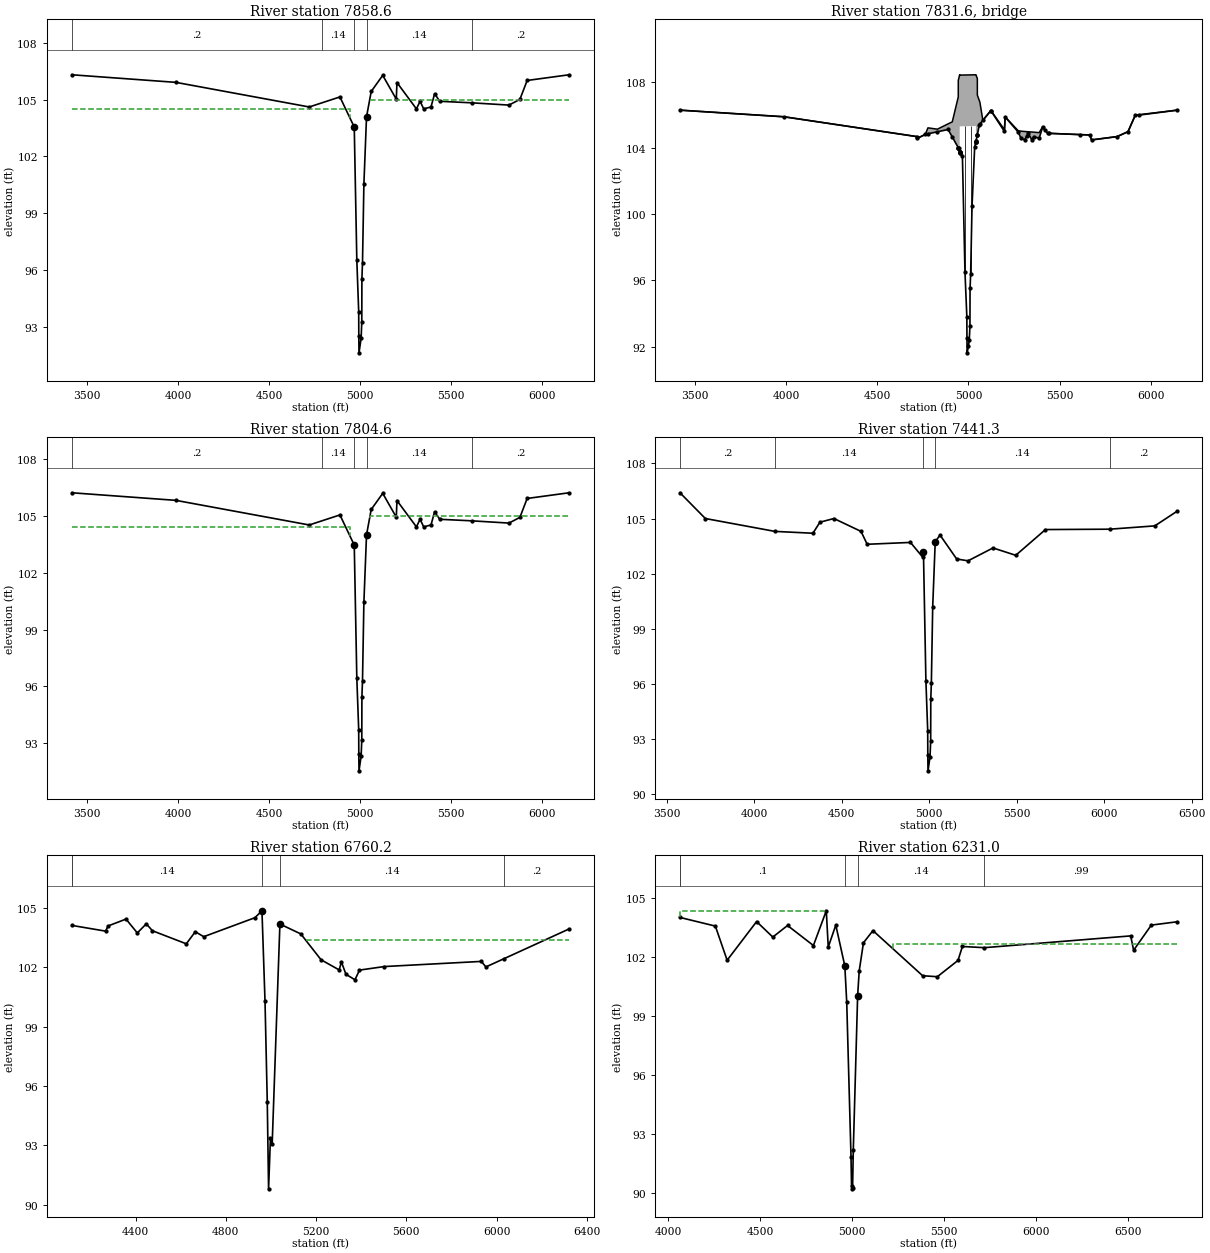
Type RM Length L Ch R = 1 ,7858.6  ,54,54,54
BEGIN DESCRIPTION:
Upstream Section of Bridge/Culvert/Weir
END DESCRIPTION:
XS GIS Cut Line= 6
      3096010.99     13926583.06      3095437.68     13926415.57
      3094633.82     13926226.66      3094386.55     13926090.35
      3094058.71     13925941.33       3093402.6     13926048.42
#Sta/Elev= 30
    3416  106.31  3987.1  105.91  4719.7  104.61  4888.1  105.14  4966.8  103.55
  4980.9   96.52  4991.2   93.81  4991.8    92.5  4992.9   91.63  5004.5    92.4
  5008.2   93.26  5008.8   95.53  5012.1   96.39  5019.7  100.52  5034.2  104.09
    5060  105.43  5123.2  106.28  5197.7  105.02  5201.3   105.9  5308.2  104.51
  5328.2  104.91  5348.2  104.51  5388.2  104.61  5408.2  105.31  5436.3  104.91
  5610.8  104.83  5816.3  104.71  5876.3  105.01  5916.3  106.01  6146.3  106.31
#Mann= 5 , 1 , 0
    3416      .2       0  4789.1     .14       0  4966.8     .05       0
  5034.2     .14       0  5610.8      .2       0
#XS Ineff= 2 , 0
       0  4942.2   104.5  5051.1       0     105
Permanent Ineff=
       F       F
Bank Sta=4966.8,5034.2
XS Rating Curve= 0
Exp/Cntr=.5,.3

Type RM Length L Ch R = 3 ,7831.6  ,,,
BEGIN DESCRIPTION:
WEST RICHEY ROAD
Structure ID: P43-04
END DESCRIPTION:
Bridge Culvert--1,0,-1,-1, 0
Deck Dist Width WeirC Skew NumUp NumDn MinLoCord MaxHiCord MaxSubmerge Is_Ogee
10,34,2.6,0, 41, 41, , , .95, 0, 1,1,,
    3416  3987.1  4717.1  4719.7    4763  4777.6  4829.3  4888.1  4911.1 4944.09
  4944.2  4951.7 4951.91    4952 5041.09  5041.2  5041.3  5048.8 5048.91    5060
  5062.9  5079.1  5123.2  5197.7  5201.3  5273.7  5288.2  5308.2  5328.2  5348.2
  5358.2  5388.2  5408.2  5418.2  5436.3  5666.3  5676.3  5816.3  5876.3  5916.3
  6146.3
   106.3   105.9   104.7   104.6  104.83  105.23  105.15  105.47  105.59   107.1
   108.1  108.44  108.42  108.42  108.44  108.44  108.44  108.21  107.21  106.87
  106.78  105.69  106.28  105.12   105.9  105.05  105.03  105.01  104.99  104.98
  104.97  104.94  105.31  105.11   104.9   104.8   104.5   104.7     105     106
   106.3
   106.3   105.9   104.7   104.6  104.83  104.87  104.99  105.13  104.68  104.03
  104.02  103.76  103.75  105.32  105.34  104.41  104.42  104.82  104.82  105.42
  105.46  105.68  106.27  105.01  105.89  104.97   104.6   104.5   104.9   104.5
   104.7   104.6   105.3   105.1   104.9   104.8   104.5   104.7     105     106
   106.3
    3416  3987.1  4717.1  4719.7    4763  4777.6  4829.3  4888.1  4911.1 4944.09
  4944.2  4951.7 4951.91    4952 5041.09  5041.2  5041.3  5048.8 5048.91    5060
  5062.9  5079.1  5123.2  5197.7  5201.3  5273.7  5288.2  5308.2  5328.2  5348.2
  5358.2  5388.2  5408.2  5418.2  5436.3  5666.3  5676.3  5816.3  5876.3  5916.3
  6146.3
   106.3   105.9   104.7   104.6  104.83  105.23  105.15  105.47  105.59   107.1
   108.1  108.44  108.42  108.42  108.44  108.44  108.44  108.21  107.21  106.87
  106.78  105.69  106.28  105.12   105.9  105.05  105.03  105.01  104.99  104.98
  104.97  104.94  105.31  105.11   104.9   104.8   104.5   104.7     105     106
   106.3
  106.23  105.83  104.63  104.53  104.76   104.8  104.92  105.06  104.61  103.96
  103.95  103.69  103.68  105.25  105.27  104.34  104.35  104.75  104.75  105.35
  105.39  105.61   106.2  104.94  105.82   104.9  104.53  104.43  104.83  104.43
  104.63  104.53  105.23  105.03  104.83  104.73  104.43  104.63  104.93  105.93
  106.23
Pier Skew, UpSta & Num, DnSta & Num=  ,4981, 2 ,4981, 2 , 0 , 0 , 0 ,,
     1.4     1.4
    95.3  106.33
     1.4     1.4
   95.23  106.26
Pier Skew, UpSta & Num, DnSta & Num=  ,5012.1, 2 ,5012.1, 2 , 0 , 0 , 0 ,,
     1.4     1.4
    95.2  106.33
     1.4     1.4
   95.13  106.26
BR Coef= 1 , 1 , 0 ,1.25, 0 ,,,.8,0,2,0,
WSPro=,,,, 1 ,,,, 0 ,,,, 0 ,,,,-1 ,-1 ,-1 , 0 , 0 , 0 , 0 , 0
BR U #Sta/Elev= 66
    3416   106.3  3987.1   105.9  4717.1   104.7  4719.7   104.6    4763  104.83
  4777.6  104.87  4829.3  104.99  4888.1  105.13  4911.1  104.68 4944.09  104.03
  4944.2  104.02 4944.31  104.02  4945.9  103.99  4951.7  103.76  4951.8  103.76
 4951.91  103.75    4952  103.75  4952.5  103.73  4952.6  103.73  4966.8  103.54
  4980.9   96.51  4991.2    93.8  4991.8   92.49  4992.9   91.62  4999.6   92.01
  5004.5   92.39  5008.2   93.25  5008.8   95.52  5012.1   96.38  5019.7  100.51
  5034.2  104.08  5040.9   104.4    5041   104.4 5041.09   104.4  5041.2  104.41
  5041.3  104.42 5048.69  104.81  5048.8  104.82 5048.91  104.82    5060  105.42
  5062.9  105.46  5079.1  105.68  5121.4  106.25  5123.2  106.27  5197.7  105.01
  5201.3  105.89  5273.7  104.97  5288.2   104.6  5308.2   104.5  5321.4  104.76
  5328.2   104.9  5348.2   104.5  5358.2   104.7  5388.2   104.6  5408.2   105.3
  5418.2   105.1  5436.3   104.9  5441.4   104.9  5610.8  104.82  5666.3   104.8
  5676.3   104.5  5816.3   104.7  5876.3     105  5916.3     106  5936.3     106
  6146.3   106.3
BR U #Mann= 5
    3416      .2  4789.1     .14  4966.8     .05  5034.2     .14  5610.8      .2
BR U Banks=4966.8,5034.2
BR D #Sta/Elev= 66
    3416  106.23  3987.1  105.83  4717.1  104.63  4719.7  104.53    4763  104.76
  4777.6   104.8  4829.3  104.92  4888.1  105.06  4911.1  104.61 4944.09  103.96
  4944.2  103.95 4944.31  103.95  4945.9  103.92  4951.7  103.69  4951.8  103.69
 4951.91  103.68    4952  103.68  4952.5  103.66  4952.6  103.66  4966.8  103.47
  4980.9   96.44  4991.2   93.73  4991.8   92.42  4992.9   91.55  4999.6   91.94
  5004.5   92.32  5008.2   93.18  5008.8   95.45  5012.1   96.31  5019.7  100.44
  5034.2  104.01  5040.9  104.33    5041  104.33 5041.09  104.33  5041.2  104.34
  5041.3  104.35 5048.69  104.74  5048.8  104.75 5048.91  104.75    5060  105.35
  5062.9  105.39  5079.1  105.61  5121.4  106.18  5123.2   106.2  5197.7  104.94
  5201.3  105.82  5273.7   104.9  5288.2  104.53  5308.2  104.43  5321.4  104.69
  5328.2  104.83  5348.2  104.43  5358.2  104.63  5388.2  104.53  5408.2  105.23
  5418.2  105.03  5436.3  104.83  5441.4  104.83  5610.8  104.75  5666.3  104.73
  5676.3  104.43  5816.3  104.63  5876.3  104.93  5916.3  105.93  5936.3  105.93
  6146.3  106.23
BR D #Mann= 5
    3416      .2  4789.1     .14  4966.8     .05  5034.2     .14  5610.8      .2
BR D Banks=4966.8,5034.2
BC Design=,, 0 ,, 0 ,,,,,,
BC HTab HWMax=106.31

Type RM Length L Ch R = 1 ,7804.6  ,363.3,363.3,363.3
BEGIN DESCRIPTION:
Downstream Section of Bridge/Culvert/Weir
END DESCRIPTION:
XS GIS Cut Line= 6
      3096041.46     13926538.47      3095468.14     13926370.99
      3094664.28     13926182.08      3094417.01     13926045.77
      3094089.17     13925896.75      3093433.06     13926003.83
#Sta/Elev= 30
    3416  106.22  3987.1  105.82  4719.7  104.52  4888.1  105.05  4966.8  103.46
  4980.9   96.43  4991.2   93.72  4991.8   92.41  4992.9   91.54  5004.5   92.31
  5008.2   93.17  5008.8   95.44  5012.1    96.3  5019.7  100.43  5034.2     104
    5060  105.34  5123.2  106.19  5197.7  104.93  5201.3  105.81  5308.2  104.42
  5328.2  104.82  5348.2  104.42  5388.2  104.52  5408.2  105.22  5436.3  104.82
  5610.8  104.74  5816.3  104.62  5876.3  104.92  5916.3  105.92  6146.3  106.22
#Mann= 5 , 1 , 0
    3416      .2       0  4789.1     .14       0  4966.8     .05       0
  5034.2     .14       0  5610.8      .2       0
#XS Ineff= 2 , 0
       0  4942.2   104.4  5051.1       0     105
Permanent Ineff=
       F       F
Bank Sta=4966.8,5034.2
XS Rating Curve= 0
Exp/Cntr=.5,.3

Type RM Length L Ch R = 1 ,7441.3  ,679.7,681.1,688.7
BEGIN DESCRIPTION:
Cross Section 7441.3-Interpolated
END DESCRIPTION:
XS GIS Cut Line= 6
      3095974.66     13926341.82      3094940.65     13925843.98
      3094729.19      13925784.4      3094605.08     13925747.97
      3094390.06     13925689.89      3093269.67      13925613.1
#Sta/Elev= 30
  3575.1   106.4  3720.1     105  4117.9   104.3  4335.1   104.2  4375.1   104.8
  4455.1     105  4610.1   104.3  4645.1   103.6  4892.7   103.7  4962.4   102.9
  4966.8   103.2  4980.9   96.17  4991.2   93.46  4991.8   92.15  4992.9   91.28
  5004.5   92.05  5008.2   92.91  5008.8   95.18  5012.1   96.04  5019.7  100.17
  5034.2  103.74  5061.7   104.1  5156.8   102.8  5221.8   102.7  5364.5   103.4
  5494.5     103  5664.5   104.4  6031.3  104.42  6289.5   104.6  6417.5   105.4
#Mann= 5 , 1 , 0
  3575.1      .2       0  4117.9     .14       0  4966.8     .04       0
  5034.2     .14       0  6031.3      .2       0
#XS Ineff= 2 , 0
       0  4455.1     105  5061.7       0   104.1
Permanent Ineff=
       F       F
Bank Sta=4966.8,5034.2
XS Rating Curve= 0
Exp/Cntr=.3,.1

Type RM Length L Ch R = 1 ,6760.2  ,532.3,529.2,516.5
BEGIN DESCRIPTION:
Cross Section 6760.2
END DESCRIPTION:
XS GIS Cut Line= 5
      3095645.41     13925460.04      3095337.37     13925279.65
      3095123.68     13925201.94      3094668.55     13925049.31
      3093540.36     13924896.23
#Sta/Elev= 30
  4117.9  104.12  4267.9  103.83  4277.9  104.09  4357.9  104.44  4407.9  103.74
  4447.9   104.2  4474.9  103.85  4624.9  103.19  4664.9   103.8  4702.3  103.55
 4929.05  104.51 4960.25  104.86 4973.75  100.29 4983.75   95.21 4989.55    90.8
 4997.85   93.37 5005.55   93.08 5039.75  104.19  5132.3  103.69  5222.3  102.38
  5302.3  101.87  5312.3  102.27  5332.3  101.65  5372.3  101.37  5392.3  101.86
  5502.3  102.04  5932.3   102.3  5952.3  102.02  6031.3  102.43  6320.8  103.94
#Mann= 5 , 1 , 0
  4117.9      .2       0  4117.9     .14       0 4960.25     .04       0
 5039.75     .14       0  6031.3      .2       0
#XS Ineff= 2 , 0
       0                 5154.95       0   103.4
Permanent Ineff=
       F       F
Bank Sta=4960.25,5039.75
XS Rating Curve= 0
Exp/Cntr=.3,.1

Type RM Length L Ch R = 1 ,6231.0  ,15.8,15.8,15.8
BEGIN DESCRIPTION:
Cross Section 6231.0
Located At: SUN PRARIE ROAD
END DESCRIPTION:
XS GIS Cut Line= 6
       3095866.1     13924824.45      3094992.42     13924599.92
      3094875.85     13924571.73      3094743.83     13924541.12
      3094252.25     13924462.82      3093241.09     13924724.83
#Sta/Elev= 30
  4065.6  104.02  4257.6  103.58  4321.6  101.84  4481.6  103.81  4569.6  103.02
  4649.6  103.61    4790  102.59    4860  104.36  4870.6  102.51  4911.6  103.63
  4960.6  101.55    4971   99.69  4994.2   91.83  4997.1   90.32  5000.4   90.19
  5002.8   90.25  5006.6   92.16  5030.2  100.03  5038.8   101.3  5061.8  102.73
  5113.3  103.35  5383.1  101.05  5463.1     101  5575.1  101.83  5599.1  102.54
  5718.6  102.48  6512.9  103.08  6528.9  102.35  6624.9  103.63  6765.4   103.8
#Mann= 5 , 1 , 0
  4065.6      .2       0  4065.6      .1       0  4960.6     .04       0
  5030.2     .14       0  5718.6     .99       0
#XS Ineff= 2 , 0
       0    4860  104.36  5223.1       0  102.66
Permanent Ineff=
       F       F
Bank Sta=4960.6,5030.2
XS Rating Curve= 0
Exp/Cntr=.7,.5