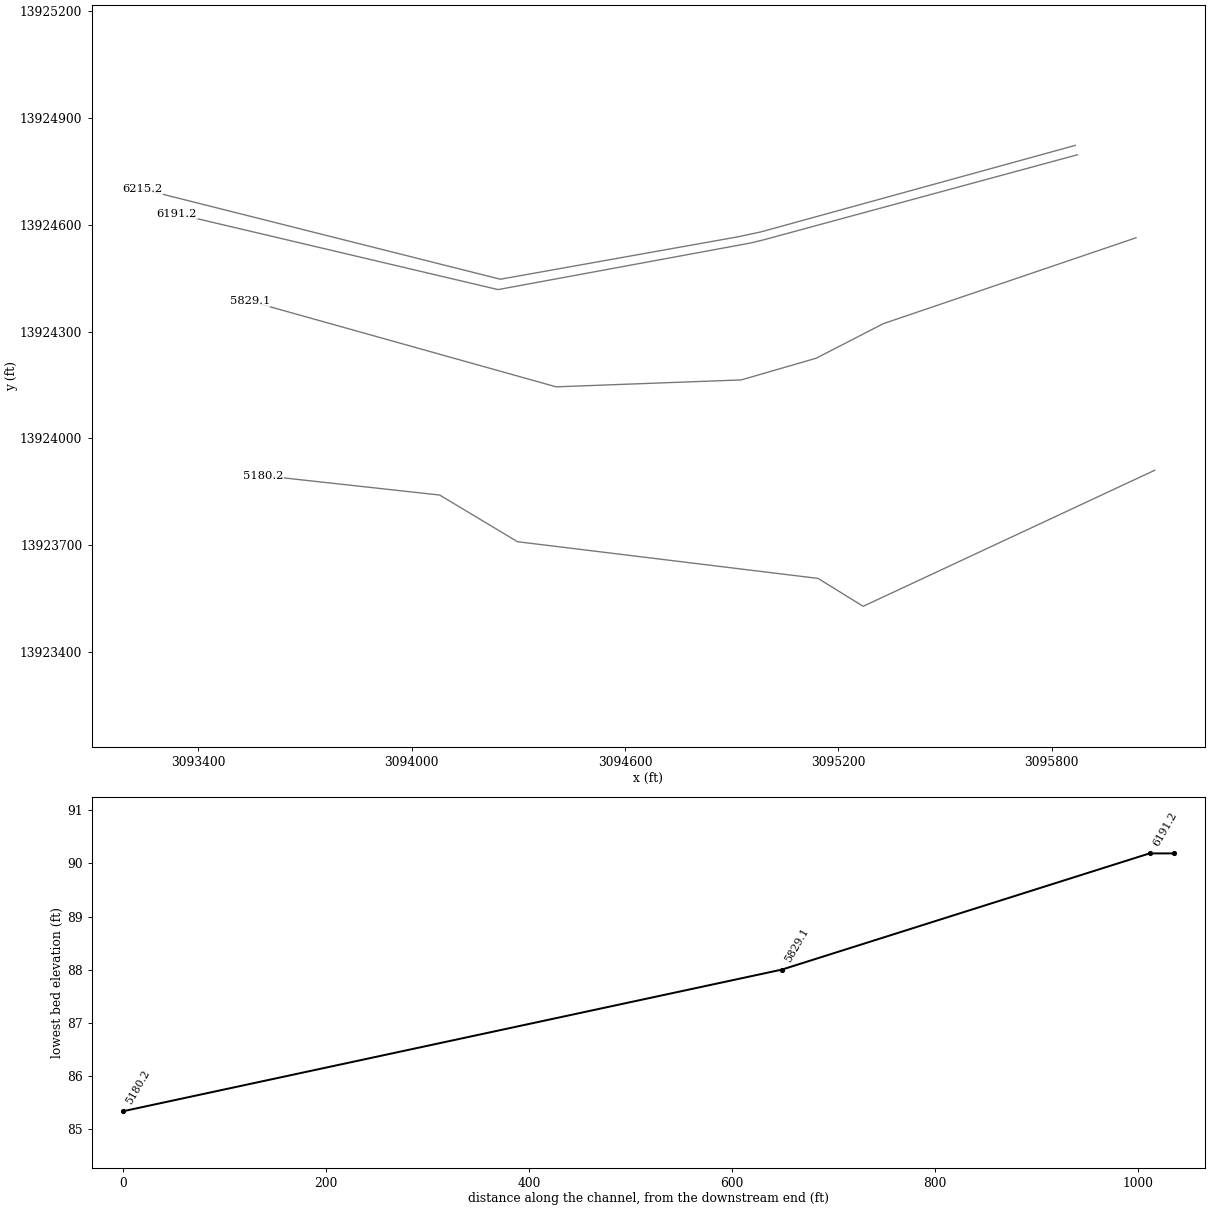
HEC-RAS study P145-03-00.prj: P145-03-00

--- P145-03-00.g03 (geometry) --- (continued)

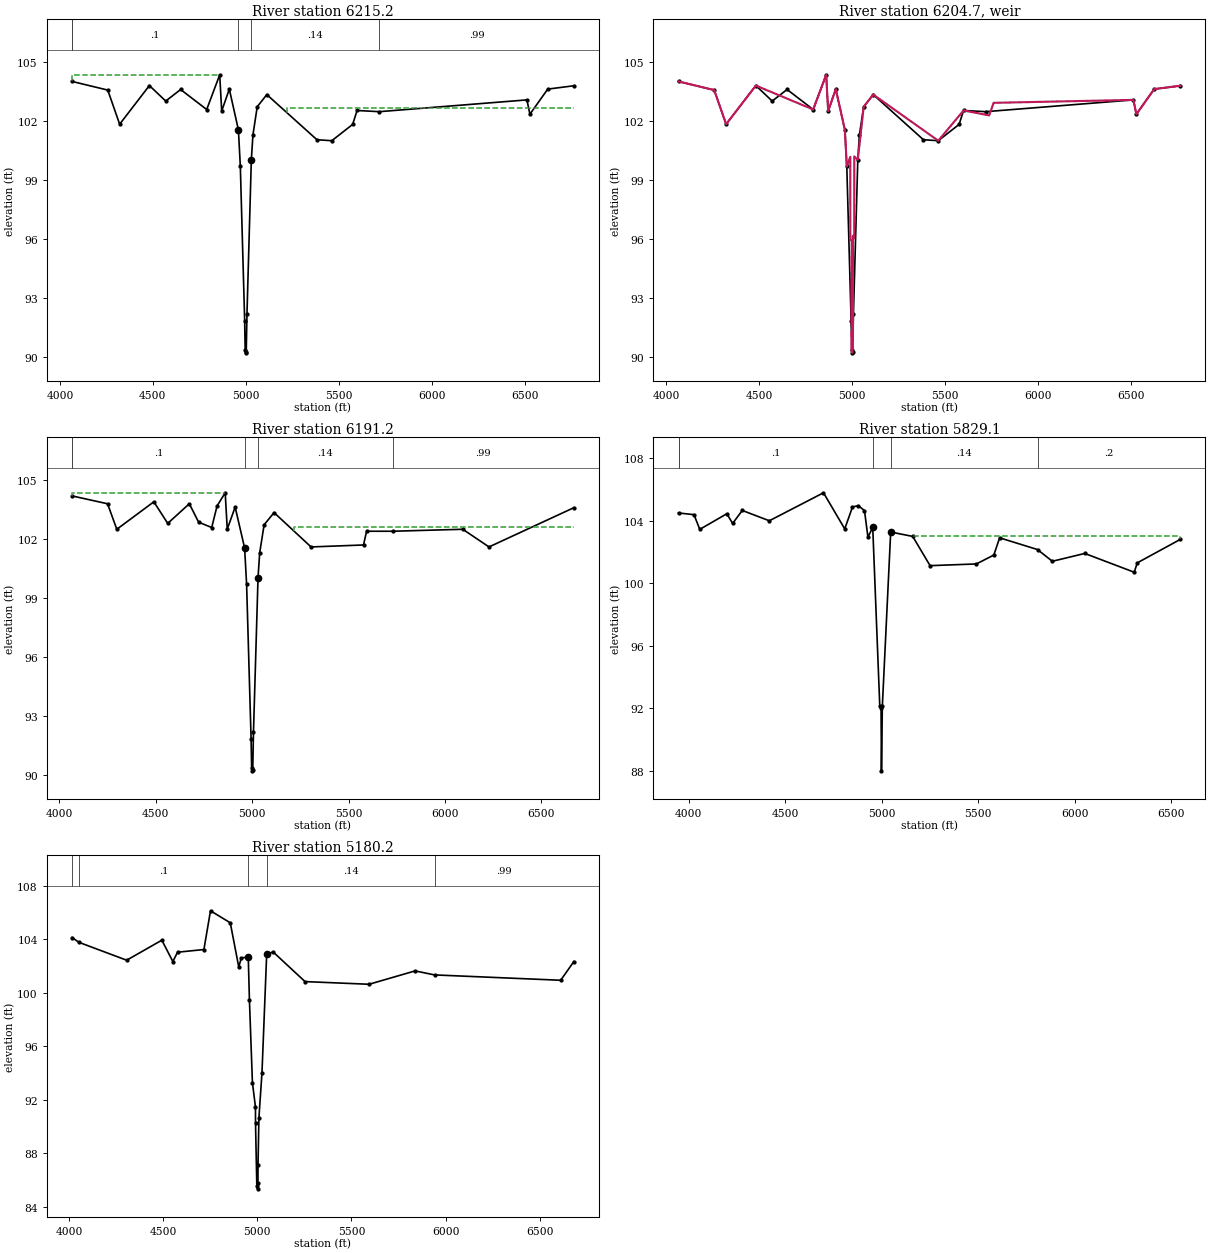
Type RM Length L Ch R = 1 ,6215.2  ,24,24,24
BEGIN DESCRIPTION:
Upstream Section of Bridge/Culvert/Weir
END DESCRIPTION:
XS GIS Cut Line= 5
      3095865.83      13924823.4      3094982.25     13924580.23
      3094915.31     13924565.96      3094249.41     13924447.13
      3093242.31     13924700.59
#Sta/Elev= 30
  4065.6  104.02  4257.6  103.58  4321.6  101.84  4481.6  103.81  4569.6  103.02
  4649.6  103.61    4790  102.59    4860  104.36  4870.6  102.51  4911.6  103.63
  4960.6  101.55  4970.9   99.69  4994.2   91.83    4997   90.32  5000.3   90.19
  5002.7   90.25  5006.6   92.16  5030.1  100.03  5038.8   101.3  5061.8  102.73
  5113.3  103.35  5383.1  101.05  5463.1     101  5575.1  101.83  5599.1  102.54
  5718.6  102.48  6512.9  103.08  6528.9  102.35  6624.9  103.63  6765.4   103.8
#Mann= 5 , 1 , 0
  4065.6      .2       0  4065.6      .1       0  4960.6     .04       0
  5030.1     .14       0  5718.6     .99       0
#XS Ineff= 2 , 0
       0    4860  104.36  5223.1       0  102.66
Permanent Ineff=
       F       F
Bank Sta=4960.6,5030.1
XS Rating Curve= 0
Exp/Cntr=.5,.3

Type RM Length L Ch R = 5 ,6204.7  ,,,
BEGIN DESCRIPTION:
SHEETPILE WEIR
Structure ID: U00-1
END DESCRIPTION:
IW Pilot Flow=0
#Inline Weir SE= 30
  4065.6  104.02  4257.6  103.58  4321.6  101.84  4481.6  103.81    4790  102.59
    4860  104.36  4870.6  102.51  4911.6  103.63  4960.6  101.55  4970.9   99.69
  4989.6  100.18  4990.1   95.94  4996.9   95.93  4997.1   90.32  5000.3   90.19
  5002.8   90.31    5004   96.15  5010.8   96.02  5011.1   100.2  5030.1  100.03
  5061.8  102.73  5113.3  103.35  5463.1     101  5599.1  102.54  5736.9  102.29
  5760.9  102.93  6512.9  103.08  6528.9  102.35  6624.9  103.63  6765.4   103.8
IW Dist,WD,Coef,Skew,MaxSub,Min_El,Is_Ogee,SpillHt,DesHd
10,1,3,0,.95,, 0 ,,,2,2,

Type RM Length L Ch R = 1 ,6191.2  ,361.5,362.1,368.6
BEGIN DESCRIPTION:
Cross Section 6191.2-Interpolated
Located At: SUN PRARIE ROAD
END DESCRIPTION:
XS GIS Cut Line= 5
      3095871.77     13924796.95      3094990.02     13924557.95
      3094953.54     13924549.07      3094242.89     13924417.97
      3093339.54     13924630.86
#Sta/Elev= 30
    4066   104.2    4250   103.8    4298   102.5    4490   103.9    4562   102.8
    4674   103.8  4722.3  102.86    4790  102.59  4817.9  103.69    4860  104.36
  4870.6  102.51  4911.6  103.63  4960.6  101.55    4971   99.69  4994.2   91.83
  4997.1   90.32  5000.4   90.19  5002.8   90.25  5006.6   92.16  5030.2  100.03
  5038.8   101.3  5061.8  102.73  5113.3  103.35  5305.1   101.6  5577.1   101.7
  5593.1   102.4  5727.6   102.4  6091.8   102.5  6227.8   101.6  6667.8   103.6
#Mann= 5 , 1 , 0
    4066      .2       0    4066      .1       0  4960.6     .04       0
  5030.2     .14       0  5727.6     .99       0
#XS Ineff= 2 , 0
       0    4860  104.36  5217.1       0   102.6
Permanent Ineff=
       F       F
Bank Sta=4960.6,5030.2
XS Rating Curve= 0
Exp/Cntr=.5,.3

Type RM Length L Ch R = 1 ,5829.1  ,649.7,648.9,595.5
BEGIN DESCRIPTION:
Cross Section 5829.1
END DESCRIPTION:
XS GIS Cut Line= 6
      3096036.72     13924563.65      3095326.27     13924322.21
      3095137.55     13924225.07      3094926.64     13924164.02
      3094406.28     13924144.57      3093544.68     13924385.66
#Sta/Elev= 30
  3948.2  104.49  4028.2  104.38  4058.2  103.44  4198.2  104.44  4228.2  103.82
  4278.2  104.65  4418.2  103.99  4698.6  105.78  4808.6  103.47  4848.6  104.87
  4878.6  104.96  4910.8  104.64 4928.65  102.95 4953.55  103.56 4989.95   92.15
 4996.55   92.04 4998.65      88 5003.25   92.14 5046.45  103.27  5160.4  102.99
  5250.4  101.12  5490.4  101.23  5580.4   101.8  5610.4   102.9  5806.5  102.15
  5883.1   101.4  6051.1   101.9  6307.1   100.7  6323.1   101.3  6545.8   102.8
#Mann= 5 , 1 , 0
  3948.2      .2       0  3948.2      .1       0 4953.55     .04       0
 5046.45     .14       0  5806.5      .2       0
#XS Ineff= 2 , 0
       0                  5160.4       0  102.99
Permanent Ineff=
       F       F
Bank Sta=4953.55,5046.45
XS Rating Curve= 0
Exp/Cntr=.5,.3

Type RM Length L Ch R = 1 ,5180.2  ,21,21,21
BEGIN DESCRIPTION:
Upstream Section of Bridge/Culvert/Weir
END DESCRIPTION:
XS GIS Cut Line= 6
      3096089.48      13923910.1      3095269.52      13923527.5
      3095142.79     13923605.95      3094297.67     13923709.14
      3094078.73     13923840.36      3093581.74     13923895.01
#Sta/Elev= 30
  4016.6  104.14  4052.7  103.78  4306.6  102.44  4493.4  103.94  4551.7  102.34
  4576.7  103.04  4716.7  103.24  4751.7  106.14  4856.7  105.24  4901.7  101.94
 4915.64  102.61 4952.24  102.68 4958.34   99.49 4974.34   93.27 4990.44   91.45
 4990.74   90.25 4997.74   85.51 5001.34   85.33 5003.64   85.79 5004.04   87.12
 5008.84   90.66 5025.04   94.02 5050.04  102.89 5084.14  103.06  5253.7  100.84
  5593.7  100.64  5838.1  101.64  5941.4  101.34  6611.2  100.94  6681.2  102.34
#Mann= 5 , 1 , 0
  4016.6      .2       0  4052.7      .1       0 4952.24     .04       0
 5050.04     .14       0  5941.4     .99       0
#XS Ineff= 2 , 0
       0 4957.67    99.8  5046.9       0   101.5
Permanent Ineff=
       F       F
Bank Sta=4952.24,5050.04
XS Rating Curve= 0
Exp/Cntr=.5,.3