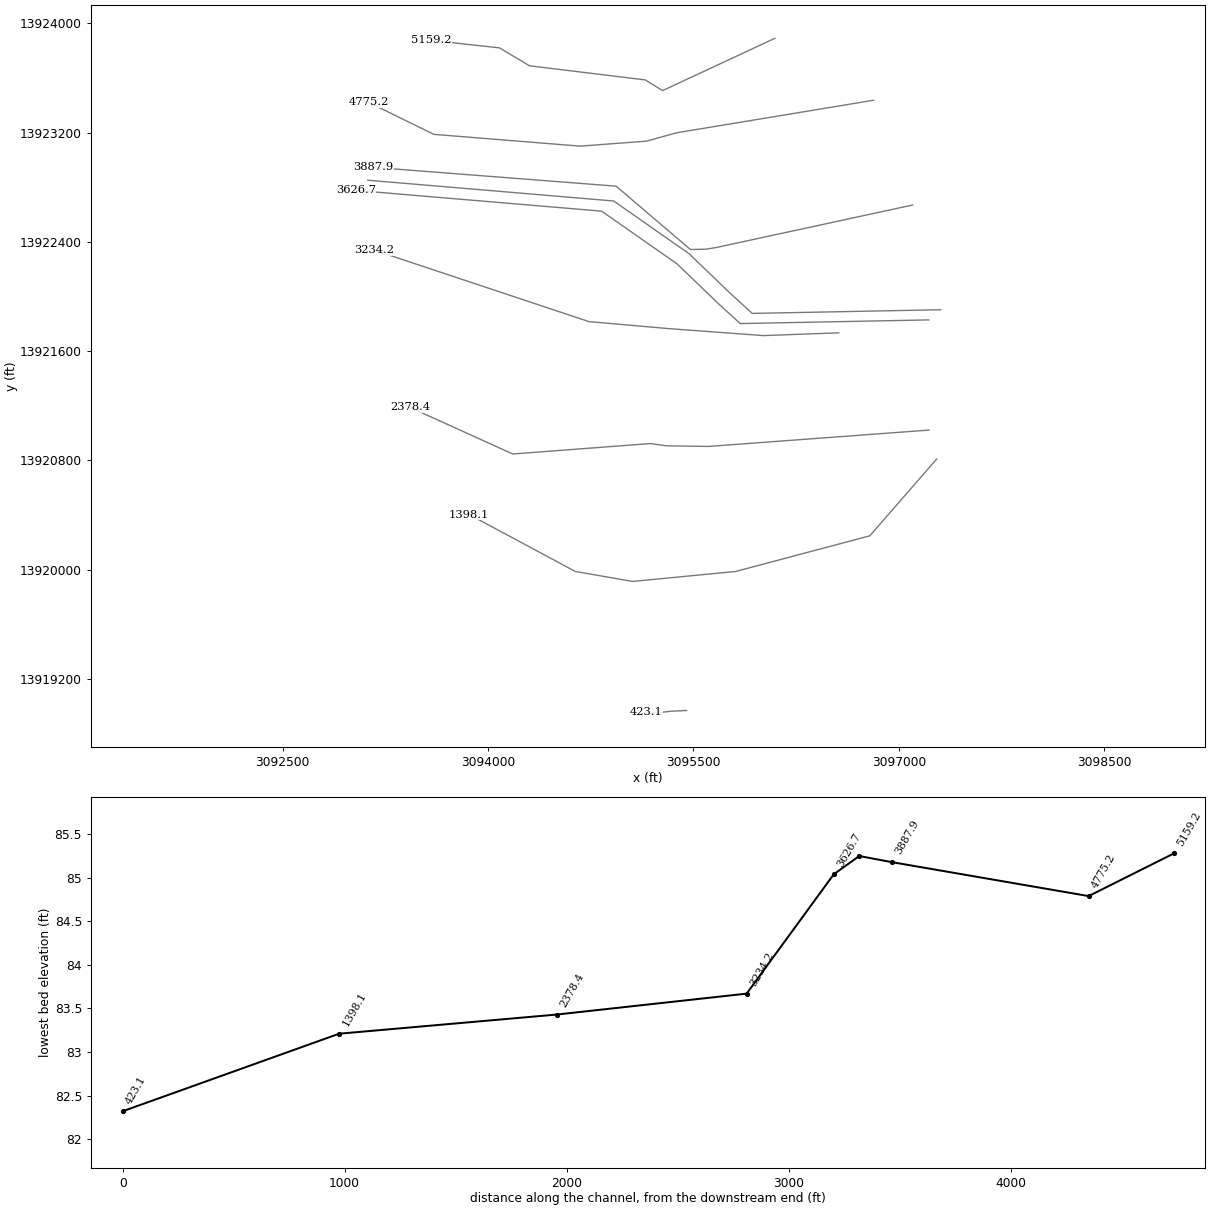
HEC-RAS study P145-03-00.prj: P145-03-00

--- P145-03-00.g03 (geometry) --- (continued)

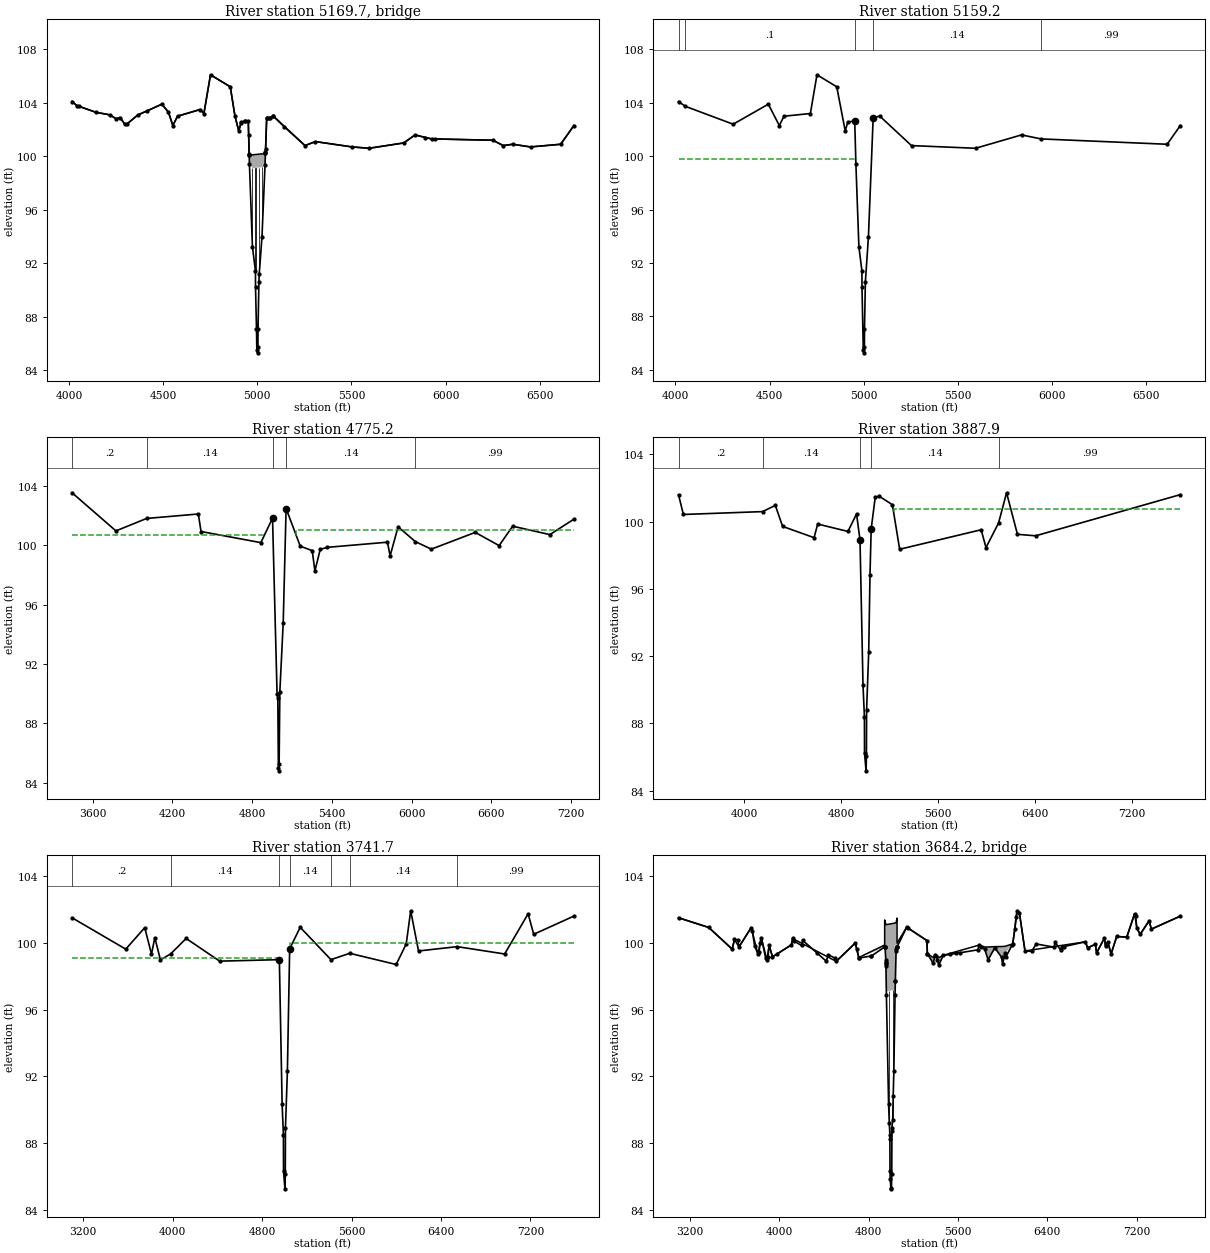
Type RM Length L Ch R = 3 ,5169.7  ,,,
BEGIN DESCRIPTION:
PIPELINE
END DESCRIPTION:
Bridge Culvert--1,0,-1,-1, 0
Deck Dist Width WeirC Skew NumUp NumDn MinLoCord MaxHiCord MaxSubmerge Is_Ogee
10,1,2.6,0, 43, 43, , , .95, 0, 1,1,,
  4016.6  4041.6  4141.6  4216.6  4251.6  4271.6  4296.6  4306.6  4366.6  4493.4
  4528.4  4551.7  4576.7  4696.7  4716.7  4751.7  4856.7  4881.7  4901.7 4915.64
 4952.24 4957.14 4958.34 4974.34 5025.04 5041.14 5043.43 5050.04 5066.24 5084.14
  5253.7  5308.7  5503.7  5593.7  5778.1  5838.1  5925.9  6251.2  6306.2  6356.2
  6451.2  6611.2  6681.2
   104.1   103.8   103.3   103.1   102.8   102.9   102.4   102.4   103.1   103.9
   103.3   102.3     103   103.5   103.2   106.1   105.2     103   101.9  102.58
  102.65  100.09  100.09  100.11  100.18  100.21  100.24  102.86  102.84  103.03
   100.8   101.1   100.7   100.6     101   101.6   101.3   101.2   100.8   100.9
   100.7   100.9   102.3
   104.1   103.8   103.3   103.1   102.8   102.9   102.4   102.4   103.1   103.9
   103.3   102.3     103   103.5   103.2   106.1   105.2     103   101.9  102.57
  102.64  100.08   99.45   99.11   99.18   99.32  100.23  102.85  102.83  103.02
   100.8   101.1   100.7   100.6     101   101.6   101.3   101.2   100.8   100.9
   100.7   100.9   102.3
  4016.6  4041.6  4141.6  4216.6  4251.6  4271.6  4296.6  4306.6  4366.6  4493.4
  4528.4  4551.7  4576.7  4696.7  4716.7  4751.7  4856.7  4881.7  4901.7 4915.64
 4952.24 4957.14 4958.34 4974.34 5025.04 5041.14 5043.43 5050.04 5066.24 5084.14
  5253.7  5308.7  5503.7  5593.7  5778.1  5838.1  5925.9  6251.2  6306.2  6356.2
  6451.2  6611.2  6681.2
   104.1   103.8   103.3   103.1   102.8   102.9   102.4   102.4   103.1   103.9
   103.3   102.3     103   103.5   103.2   106.1   105.2     103   101.9  102.58
  102.65  100.09  100.09  100.11  100.18  100.21  100.24  102.86  102.84  103.03
   100.8   101.1   100.7   100.6     101   101.6   101.3   101.2   100.8   100.9
   100.7   100.9   102.3
   104.1   103.8   103.3   103.1   102.8   102.9   102.4   102.4   103.1   103.9
   103.3   102.3     103   103.5   103.2   106.1   105.2     103   101.9  102.57
  102.64  100.08   99.45   99.11   99.18   99.32  100.23  102.85  102.83  103.02
   100.8   101.1   100.7   100.6     101   101.6   101.3   101.2   100.8   100.9
   100.7   100.9   102.3
Pier Skew, UpSta & Num, DnSta & Num=  ,4974.3, 2 ,4974.3, 2 , 0 , 0 , 0 ,,
      .7      .7
   92.19  100.12
      .7      .7
   92.19  100.12
Pier Skew, UpSta & Num, DnSta & Num=  ,4990.4, 2 ,4990.4, 2 , 0 , 0 , 0 ,,
      .7      .7
   89.18  100.14
      .7      .7
   89.18  100.14
Pier Skew, UpSta & Num, DnSta & Num=  ,5010.3, 2 ,5010.3, 2 , 0 , 0 , 0 ,,
      .7      .7
   90.03  100.16
      .7      .7
   90.03  100.16
Pier Skew, UpSta & Num, DnSta & Num=  ,5025, 2 ,5025, 2 , 0 , 0 , 0 ,,
      .7      .7
   92.91  100.18
      .7      .7
   92.91  100.18
BR Coef= 1 , 1 , 0 ,1.25, 0 ,,,.8,0,2,0,
WSPro=,,,, 1 ,,,, 0 ,,,, 0 ,,,,-1 ,-1 ,-1 , 0 , 0 , 0 , 0 , 0
BR U #Sta/Elev= 69
  4016.6   104.1  4041.6   103.8  4052.7  103.74  4141.6   103.3  4216.6   103.1
  4251.6   102.8  4271.6   102.9  4296.6   102.4  4306.6   102.4  4366.6   103.1
  4416.6   103.4  4493.4   103.9  4528.4   103.3  4551.7   102.3  4576.7     103
  4696.7   103.5  4716.7   103.2  4751.7   106.1  4856.7   105.2  4881.7     103
  4901.7   101.9  4914.2   102.5 4915.64  102.57 4933.84  102.61  4934.2  102.61
 4952.24  102.64  4954.2  101.62 4956.94  100.18 4957.05  100.12 4957.14  100.08
 4958.34   99.45 4974.34   93.23 4990.44   91.41 4990.74   90.21 4995.94   87.06
 4997.74   85.47 5001.34   85.29 5003.64   85.75 5004.04   87.08 5008.84   90.62
 5010.34   91.16 5025.04   93.98 5041.14   99.32 5043.43  100.23 5043.54  100.27
 5043.64  100.31  5044.2  100.53 5050.04  102.85  5054.2  102.84  5064.2  102.83
 5066.24  102.83 5084.14  103.02  5084.7  103.01  5143.7   102.2  5253.7   100.8
  5308.7   101.1  5503.7   100.7  5593.7   100.6  5778.1     101  5838.1   101.6
  5893.1   101.4  5925.9   101.3  5941.4   101.3  6251.2   101.2  6306.2   100.8
  6356.2   100.9  6451.2   100.7  6611.2   100.9  6681.2   102.3
BR U #Mann= 5
  4016.6      .2  4052.7      .1 4952.24    .045 5050.04     .14  5941.4     .99
BR U Banks=4952.24,5050.04
BR D #Sta/Elev= 69
  4016.6   104.1  4041.6   103.8  4052.7  103.74  4141.6   103.3  4216.6   103.1
  4251.6   102.8  4271.6   102.9  4296.6   102.4  4306.6   102.4  4366.6   103.1
  4416.6   103.4  4493.4   103.9  4528.4   103.3  4551.7   102.3  4576.7     103
  4696.7   103.5  4716.7   103.2  4751.7   106.1  4856.7   105.2  4881.7     103
  4901.7   101.9  4914.2   102.5 4915.64  102.57 4933.84  102.61  4934.2  102.61
 4952.24  102.64  4954.2  101.62 4956.94  100.18 4957.05  100.12 4957.14  100.08
 4958.34   99.45 4974.34   93.23 4990.44   91.41 4990.74   90.21 4995.94   87.06
 4997.74   85.47 5001.34   85.29 5003.64   85.75 5004.04   87.08 5008.84   90.62
 5010.34   91.16 5025.04   93.98 5041.14   99.32 5043.43  100.23 5043.54  100.27
 5043.64  100.31  5044.2  100.53 5050.04  102.85  5054.2  102.84  5064.2  102.83
 5066.24  102.83 5084.14  103.02  5084.7  103.01  5143.7   102.2  5253.7   100.8
  5308.7   101.1  5503.7   100.7  5593.7   100.6  5778.1     101  5838.1   101.6
  5893.1   101.4  5925.9   101.3  5941.4   101.3  6251.2   101.2  6306.2   100.8
  6356.2   100.9  6451.2   100.7  6611.2   100.9  6681.2   102.3
BR D #Mann= 5
  4016.6      .2  4052.7      .1 4952.24    .045 5050.04     .14  5941.4     .99
BR D Banks=4952.24,5050.04
BC Design=,, 0 ,, 0 ,,,,,,
BC HTab HWMax=106.14

Type RM Length L Ch R = 1 ,5159.2  ,384,384,384
BEGIN DESCRIPTION:
Downstream Section of Bridge/Culvert/Weir
END DESCRIPTION:
XS GIS Cut Line= 6
       3096094.5      13923889.7      3095274.54      13923507.1
      3095147.81     13923585.55      3094302.69     13923688.74
      3094083.75     13923819.96      3093586.76     13923874.62
#Sta/Elev= 30
  4016.6  104.09  4052.7  103.73  4306.6  102.39  4493.4  103.89  4551.7  102.29
  4576.7  102.99  4716.7  103.19  4751.7  106.09  4856.7  105.19  4901.7  101.89
 4915.64  102.56 4952.24  102.63 4958.34   99.44 4974.34   93.22 4990.44    91.4
 4990.74    90.2 4997.74   85.46 5001.34   85.28 5003.64   85.74 5004.04   87.07
 5008.84   90.61 5025.04   93.97 5050.04  102.84 5084.14  103.01  5253.7  100.79
  5593.7  100.59  5838.1  101.59  5941.4  101.29  6611.2  100.89  6681.2  102.29
#Mann= 5 , 1 , 0
  4016.6      .2       0  4052.7      .1       0 4952.24     .04       0
 5050.04     .14       0  5941.4     .99       0
#XS Ineff= 2 , 0
       0 4957.67    99.8  5046.9       0   101.5
Permanent Ineff=
       F       F
Bank Sta=4952.24,5050.04
XS Rating Curve= 0
Exp/Cntr=.5,.3

Type RM Length L Ch R = 1 ,4775.2  ,1194.9,887.3,452.8
BEGIN DESCRIPTION:
Cross Section 4775.2
END DESCRIPTION:
XS GIS Cut Line= 6
      3096815.59     13923436.64      3095376.22     13923198.25
      3095156.98      13923137.2      3094672.44     13923100.72
      3093604.24     13923186.98      3093127.96     13923420.59
#Sta/Elev= 30
  3445.7  103.53  3775.7  100.96  4006.4   101.8  4395.7   102.1  4415.7  100.92
  4865.7  100.17  4953.6  101.82  4987.8   89.98  4993.3   89.71  4997.7   84.97
  5001.3   84.79  5003.2   85.25  5008.6   90.12    5034   94.77  5055.7  102.47
  5162.3   99.93  5252.3   99.63  5272.3   98.26  5312.3   99.71  5362.3   99.85
  5818.2   100.2  5838.2   99.28  5898.2  101.24  6027.6  100.24  6148.2   99.73
  6478.2  100.86  6658.2   99.97  6759.8  101.28  7039.8  100.71  7220.3  101.75
#Mann= 5 , 1 , 0
  3445.7      .2       0  4006.4     .14       0  4953.6     .04       0
  5055.7     .14       0  6027.6     .99       0
#XS Ineff= 2 , 0
       0  4887.5   100.7  5132.3       0  100.99
Permanent Ineff=
       F       F
Bank Sta=4953.6,5055.7
XS Rating Curve= 0
Exp/Cntr=.3,.1

Type RM Length L Ch R = 1 ,3887.9  ,146.2,146.2,146.2
BEGIN DESCRIPTION:
Cross Section 3887.9-Interpolated
END DESCRIPTION:
XS GIS Cut Line= 6
      3097100.62     13922669.76      3095662.94       13922358.
      3095589.84     13922346.33      3095477.77     13922344.32
      3094935.19     13922807.79      3093164.51     13922945.36
#Sta/Elev= 30
  3455.1   101.6  3495.1  100.43  4149.9   100.6  4255.1  100.97  4315.1   99.72
  4575.1   99.05  4605.1   99.86  4855.1   99.42  4926.2  100.46  4954.8   98.92
  4979.6   90.26  4991.2    88.4  4992.1   86.23  5004.9   85.18  5007.9   86.06
  5009.3   88.82  5026.7   92.23  5037.3   96.83  5047.1   99.57  5080.3  101.44
  5112.4  101.52  5222.4  101.01  5282.4   98.36  5955.9   99.52  5995.9   98.46
  6099.7   99.92  6165.9  101.72  6255.9   99.25  6405.9   99.16  7601.9  101.61
#Mann= 5 , 1 , 0
  3455.1      .2       0  4149.9     .14       0  4954.8     .04       0
  5047.1     .14       0  6099.7     .99       0
#XS Ineff= 2 , 0
       0  4926.2  100.46  5232.4       0  100.73
Permanent Ineff=
       F       F
Bank Sta=4954.8,5047.1
XS Rating Curve= 0
Exp/Cntr=.5,.3

Type RM Length L Ch R = 1 ,3741.7  ,115,115,115
BEGIN DESCRIPTION:
Upstream Section of Bridge/Culvert/Weir
END DESCRIPTION:
XS GIS Cut Line= 6
      3097306.43     13921903.35       3095929.5     13921876.52
      3095769.73      13922022.7      3095467.24     13922314.09
      3094917.34     13922699.25      3093121.89     13922851.25
#Sta/Elev= 30
  3101.3   101.5  3581.3   99.62  3751.3  100.91  3811.3   99.32  3841.3  100.31
  3891.3   98.98  3982.4   99.33  4121.3  100.26  4421.3    98.9  4954.8   98.99
  4979.6   90.33  4991.1   88.47  4992.1    86.3  5004.9   85.25  5007.9   86.13
  5009.3   88.89  5026.7    92.3  5047.1   99.64  5141.3  100.93    5416   98.99
  5583.9   99.37  5999.3    98.7  6089.3   99.93  6129.3  101.92  6199.3   99.51
  6544.7   99.77  6969.3   99.33  7179.3  101.74  7229.3  100.51  7588.3   101.6
#Mann= 7 , 1 , 0
  3101.3      .2       0  3982.4     .14       0  4954.8     .04       0
  5047.1     .14       0    5416      .1       0  5583.9     .14       0
  6544.7     .99       0
#XS Ineff= 2 , 0
       0  4945.3    99.1  5050.3       0     100
Permanent Ineff=
       F       F
Bank Sta=4954.8,5047.1
XS Rating Curve= 0
Exp/Cntr=.5,.3

Type RM Length L Ch R = 3 ,3684.2  ,,,
BEGIN DESCRIPTION:
KUYKENDAHL ROAD
Structure ID: P43-01
END DESCRIPTION:
Bridge Culvert--1,0,-1,-1, 0
Deck Dist Width WeirC Skew NumUp NumDn MinLoCord MaxHiCord MaxSubmerge Is_Ogee
10,95,2.6,0, 60, 60, , , .95, 0, 1,1,,
  3101.3  3371.3  3581.3  3601.3  3641.3  3751.3  3811.3  3841.3  3891.3  3911.3
  3941.3  4111.3  4121.3  4510.4    4682  4713.7 4944.49  4944.6  4947.4  4954.8
    4960  5026.7  5037.3  5047.1 5055.09  5055.2 5055.31  5141.3  5322.3  5326.4
  5377.9  5397.9  5427.9  5467.9  5787.9  5839.3  5869.3  5929.3  5999.3  6019.3
  6089.3  6129.3  6149.3  6199.3  6739.3  6759.3  6829.3  6839.3  6909.3  6919.3
  6939.3  6969.3  7019.3  7109.3  7179.3  7199.3  7229.3  7309.3  7329.3  7588.3
   101.5  100.92   99.62   100.2   99.75  100.91   99.32  100.31   98.98   99.85
   99.16   99.88  100.26   98.89   99.99   99.12   99.87  101.37   101.3  101.09
  101.09  101.17  101.19  101.21  101.48  101.48   99.98  100.94  100.14   99.35
   99.12    99.3   99.11   99.25   99.86   99.75   99.75   99.77   99.78   99.79
   99.93  101.92   101.8   99.51  100.06    99.7   99.91   99.39  100.28   99.79
  100.07   99.33  100.38  100.34  101.74  100.88  100.51  101.32  100.82   101.6
   101.5  100.92   99.62   100.2   99.75  100.91   99.32  100.31   98.98   99.85
   99.16   99.88  100.26   98.88   99.98   99.09   99.75   99.75   99.76   98.99
   97.09   97.17   97.19   99.64   99.75   99.75   99.75  100.93  100.13   99.34
   98.78   99.29   98.66   99.24   99.85   99.62   98.98    99.7    98.7   99.37
   99.93  101.92   101.8   99.51  100.06    99.7   99.91   99.39  100.28   99.79
  100.07   99.33  100.38  100.34  101.74  100.88  100.51  101.32  100.82   101.6
  3101.3  3371.3  3581.3  3601.3  3641.3  3751.3  3811.3  3841.3  3891.3  3911.3
  3941.3  4111.3  4121.3  4510.4    4682  4713.7 4944.49  4944.6  4947.4  4954.8
    4960  5026.7  5037.3  5047.1 5055.09  5055.2 5055.31  5141.3  5322.3  5326.4
  5377.9  5397.9  5427.9  5467.9  5787.9  5839.3  5869.3  5929.3  5999.3  6019.3
  6089.3  6129.3  6149.3  6199.3  6739.3  6759.3  6829.3  6839.3  6909.3  6919.3
  6939.3  6969.3  7019.3  7109.3  7179.3  7199.3  7229.3  7309.3  7329.3  7588.3
   101.5  100.92   99.62   100.2   99.75  100.91   99.32  100.31   98.98   99.85
   99.16   99.88  100.26   98.89   99.99   99.12   99.87  101.37   101.3  101.09
  101.09  101.17  101.19  101.21  101.48  101.48   99.98  100.94  100.14   99.35
   99.12    99.3   99.11   99.25   99.86   99.75   99.75   99.77   99.78   99.79
   99.93  101.92   101.8   99.51  100.06    99.7   99.91   99.39  100.28   99.79
  100.07   99.33  100.38  100.34  101.74  100.88  100.51  101.32  100.82   101.6
  101.32  100.74   99.44  100.02   99.57  100.73   99.14  100.13    98.8   99.67
   98.98    99.7  100.08    98.7    99.8   98.91   99.57   99.57   99.58   98.81
   96.91   96.99   97.01   99.46   99.57   99.57   99.57  100.75   99.95   99.16
    98.6   99.11   98.48   99.06   99.67   99.44    98.8   99.52   98.52   99.19
   99.75  101.74  101.62   99.33   99.88   99.52   99.73   99.21   100.1   99.61
   99.89   99.15   100.2  100.16  101.56   100.7  100.33  101.14  100.64  101.42
Pier Skew, UpSta & Num, DnSta & Num=  ,4985.9, 2 ,4985.9, 2 , 0 , 0 , 0 ,,
     1.4     1.4
   88.11   98.12
     1.4     1.4
   87.93   97.94
Pier Skew, UpSta & Num, DnSta & Num=  ,5016.4, 2 ,5016.4, 2 , 0 , 0 , 0 ,,
     1.4     1.4
   88.34   98.16
     1.4     1.4
   88.16   97.98
Abutment Skew #Up #Dn= , 2 , 2
  4955.2  4991.2
   98.75   88.25
  4955.2  4991.2
   98.57   88.07
Abutment Skew #Up #Dn= , 2 , 2
  5009.3 5040.39
   88.89   97.71
  5009.3 5040.39
   88.71   97.53
BR Coef= 1 , 1 , 0 ,1.25, 0 ,,,.8,0,2,0,
WSPro=,,,, 1 ,,,, 0 ,,,, 0 ,,,,-1 ,-1 ,-1 , 0 , 0 , 0 , 0 , 0
BR U #Sta/Elev= 122
  3101.3   101.5  3371.3  100.92  3581.3   99.62  3601.3   100.2  3631.3  100.17
  3641.3   99.75  3751.3  100.91  3761.3  100.71  3781.3   99.83  3811.3   99.32
  3821.3   99.47  3831.3  100.01  3841.3  100.31  3881.3   99.07  3891.3   98.98
  3901.3   99.14  3911.3   99.85  3941.3   99.16  3982.4   99.33  4111.3   99.88
  4121.3  100.26  4131.3  100.11  4201.3   99.84  4211.3  100.15  4341.5   99.38
  4421.3    98.9  4441.3   99.28  4500.4   99.08  4510.4   98.88    4682   99.98
  4695.1   99.61  4713.7   99.09  4715.3   99.09  4825.2   99.21  4826.1   99.21
 4944.49   99.75  4944.6   99.75 4944.71   99.75  4947.4   99.76  4954.8   98.99
  4955.2   98.83 4955.31   98.79  4955.4   98.75  4955.7   98.63    4960    96.9
  4979.6   90.33  4985.9   89.21  4991.1   88.47  4991.2   88.25  4992.1    86.3
  4994.6   85.82  5000.1   85.29  5004.9   85.25  5007.9   86.13  5009.2   88.69
  5009.3   88.89  5016.4   89.39  5020.8   90.82  5026.7    92.3  5037.3    96.9
 5040.19   97.71  5040.3   97.74  5046.7   99.53  5047.1   99.64 5055.09   99.75
  5055.2   99.75 5055.31   99.75  5141.3  100.93  5153.4  100.88  5322.3  100.13
  5326.4   99.34  5326.5   99.34  5377.9   98.78  5397.9   99.29  5407.9   99.22
    5416   98.99  5427.9   98.66  5467.9   99.24  5525.1    99.3  5583.9   99.37
  5615.1    99.4  5777.9   99.58  5787.9   99.85  5809.3   99.74  5839.3   99.62
  5869.3   98.98  5929.3    99.7  5989.3   99.14  5999.3    98.7  6019.3   99.37
  6029.3   99.16  6083.5   99.86  6089.3   99.93  6109.3  100.82  6119.3  101.56
  6129.3  101.92  6149.3   101.8  6199.3   99.51  6259.3   99.49  6299.3   99.93
  6459.3   99.74  6469.3  100.03  6519.3   99.55  6529.3   99.75  6544.7   99.77
  6739.3  100.06  6759.3    99.7  6829.3   99.91  6839.3   99.39  6909.3  100.28
  6919.3   99.79  6939.3  100.07  6969.3   99.33  7019.3  100.38  7109.3  100.34
  7179.3  101.74  7189.3  101.58  7199.3  100.88  7229.3  100.51  7309.3  101.32
  7329.3  100.82  7588.3   101.6
BR U #Mann= 7
  3101.3      .2  3982.4     .14  4954.8     .04  5047.1     .14    5416      .1
  5583.9     .14  6544.7     .99
BR U Banks=4954.8,5047.1
BR D #Sta/Elev= 122
  3101.3  101.32  3371.3  100.74  3581.3   99.44  3601.3  100.02  3631.3   99.99
  3641.3   99.57  3751.3  100.73  3761.3  100.53  3781.3   99.65  3811.3   99.14
  3821.3   99.29  3831.3   99.83  3841.3  100.13  3881.3   98.89  3891.3    98.8
  3901.3   98.96  3911.3   99.67  3941.3   98.98  3982.4   99.15  4111.3    99.7
  4121.3  100.08  4131.3   99.93  4201.3   99.66  4211.3   99.97  4341.5    99.2
  4421.3   98.72  4441.3    99.1  4500.4    98.9  4510.4    98.7    4682    99.8
  4695.1   99.43  4713.7   98.91  4715.3   98.91  4825.2   99.03  4826.1   99.03
 4944.49   99.57  4944.6   99.57 4944.71   99.57  4947.4   99.58  4954.8   98.81
  4955.2   98.65 4955.31   98.61  4955.4   98.57  4955.7   98.45    4960   96.72
  4979.6   90.15  4985.9   89.03  4991.1   88.29  4991.2   88.07  4992.1   86.12
  4994.6   85.64  5000.1   85.11  5004.9   85.07  5007.9   85.95  5009.2   88.51
  5009.3   88.71  5016.4   89.21  5020.8   90.64  5026.7   92.12  5037.3   96.72
 5040.19   97.53  5040.3   97.56  5046.7   99.35  5047.1   99.46 5055.09   99.57
  5055.2   99.57 5055.31   99.57  5141.3  100.75  5153.4   100.7  5322.3   99.95
  5326.4   99.16  5326.5   99.16  5377.9    98.6  5397.9   99.11  5407.9   99.04
    5416   98.81  5427.9   98.48  5467.9   99.06  5525.1   99.12  5583.9   99.19
  5615.1   99.22  5777.9    99.4  5787.9   99.67  5809.3   99.56  5839.3   99.44
  5869.3    98.8  5929.3   99.52  5989.3   98.96  5999.3   98.52  6019.3   99.19
  6029.3   98.98  6083.5   99.68  6089.3   99.75  6109.3  100.64  6119.3  101.38
  6129.3  101.74  6149.3  101.62  6199.3   99.33  6259.3   99.31  6299.3   99.75
  6459.3   99.56  6469.3   99.85  6519.3   99.37  6529.3   99.57  6544.7   99.59
  6739.3   99.88  6759.3   99.52  6829.3   99.73  6839.3   99.21  6909.3   100.1
  6919.3   99.61  6939.3   99.89  6969.3   99.15  7019.3   100.2  7109.3  100.16
  7179.3  101.56  7189.3   101.4  7199.3   100.7  7229.3  100.33  7309.3  101.14
  7329.3  100.64  7588.3  101.42
BR D #Mann= 7
  3101.3      .2  3982.4     .14  4954.8     .04  5047.1     .14    5416      .1
  5583.9     .14  6544.7     .99
BR D Banks=4954.8,5047.1
BC Design=,, 0 ,, 0 ,,,,,,
BC HTab HWMax=101.92

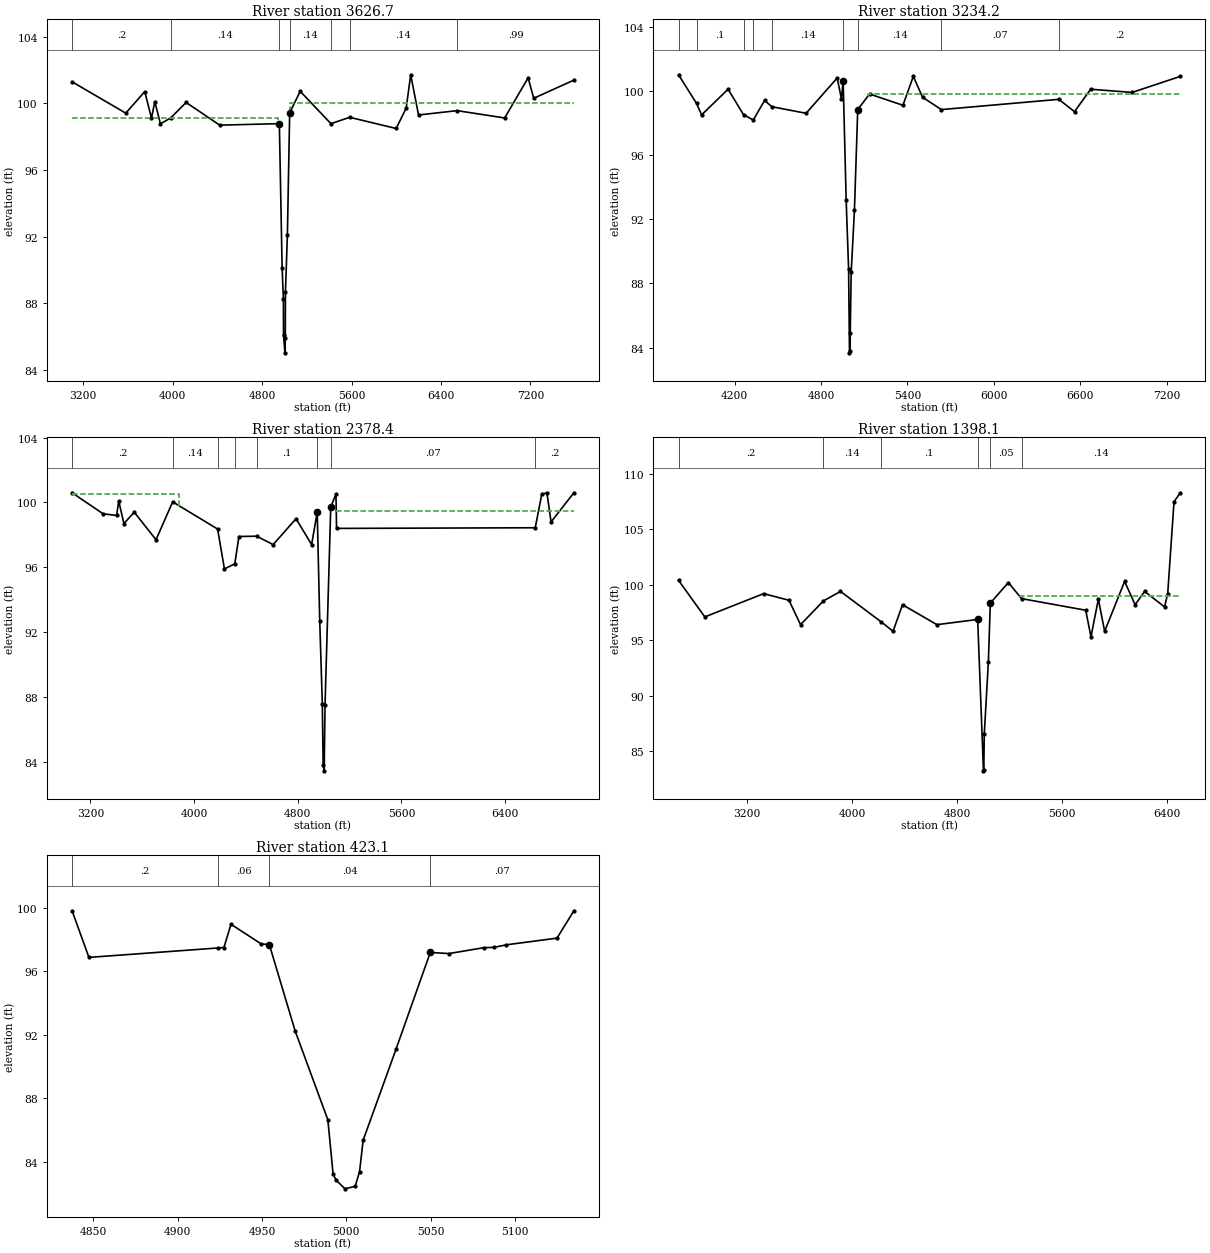
Type RM Length L Ch R = 1 ,3626.7  ,392.5,392.5,392.5
BEGIN DESCRIPTION:
Downstream Section of Bridge/Culvert/Weir
END DESCRIPTION:
XS GIS Cut Line= 6
      3097218.74     13921828.94      3095841.82     13921802.12
      3095682.05      13921948.3      3095379.56     13922239.69
      3094829.66     13922624.85       3093034.2     13922776.85
#Sta/Elev= 30
  3101.3  101.29  3581.3   99.41  3751.3   100.7  3811.3   99.11  3841.3   100.1
  3891.3   98.77  3982.4   99.12  4121.3  100.05  4421.3   98.69  4954.8   98.78
  4979.6   90.12  4991.1   88.26  4992.1   86.09  5004.9   85.04  5007.9   85.92
  5009.3   88.68  5026.7   92.09  5047.1   99.43  5141.3  100.72    5416   98.78
  5583.9   99.16  5999.3   98.49  6089.3   99.72  6129.3  101.71  6199.3    99.3
  6544.7   99.56  6969.3   99.12  7179.3  101.53  7229.3   100.3  7588.3  101.39
#Mann= 7 , 1 , 0
  3101.3      .2       0  3982.4     .14       0  4954.8     .04       0
  5047.1     .14       0    5416      .1       0  5583.9     .14       0
  6544.7     .99       0
#XS Ineff= 2 , 0
       0  4945.3    99.1  5050.3       0     100
Permanent Ineff=
       F       F
Bank Sta=4954.8,5047.1
XS Rating Curve= 0
Exp/Cntr=.5,.3

Type RM Length L Ch R = 1 ,3234.2  ,852.6,855.8,995.7
BEGIN DESCRIPTION:
Cross Section 3234.2
END DESCRIPTION:
XS GIS Cut Line= 5
      3096561.15     13921734.35      3096011.98     13921714.09
      3095317.35     13921765.33      3094736.58     13921816.58
      3093166.91     13922340.19
#Sta/Elev= 30
  3811.2     101  3936.5   99.21  3971.2    98.5  4155.2   100.1  4262.4   98.51
  4330.1   98.18  4408.7    99.4  4458.8   99.01  4696.7    98.6  4912.7   100.8
    4942    99.5    4954  100.64    4975   93.18  4991.9   88.89    4998   83.67
  5002.9   83.77  5003.3   84.93  5009.9   88.69  5032.4   92.56  5055.3   98.83
  5137.2    99.8  5369.2    99.1  5441.2   100.9  5505.2    99.6    5636   98.83
  6451.4   99.47  6560.2    98.7  6672.2   100.1  6960.2    99.9  7294.9   100.9
#Mann= 9 , 1 , 0
  3811.2      .2       0  3936.5      .1       0  4262.4     .14       0
  4330.1      .1       0  4458.8     .14       0    4954     .04       0
  5055.3     .14       0    5636     .07       0  6451.4      .2       0
#XS Ineff= 2 , 0
       0  4155.2   100.1  5128.2       0    99.8
Permanent Ineff=
       F       F
Bank Sta=4954,5055.3
XS Rating Curve= 0
Exp/Cntr=.3,.1

Type RM Length L Ch R = 1 ,2378.4  ,906,980.3,949
BEGIN DESCRIPTION:
Cross Section 2378.4
END DESCRIPTION:
XS GIS Cut Line= 6
        3097221.     13921022.61      3095608.58     13920902.83
      3095303.87     13920907.38      3095185.11     13920923.92
      3094180.43     13920847.55      3093430.25     13921188.53
#Sta/Elev= 30
  3058.2   100.6  3298.2    99.3  3402.2    99.2  3418.2   100.1  3458.2    98.7
  3538.2    99.4  3706.2    97.7  3834.7  100.04  4181.6   98.36  4234.2    95.9
  4314.1   96.21  4346.2    97.9  4482.6   97.92  4610.2    97.4  4787.1      99
  4907.1    97.4  4950.5   99.41  4969.8   92.68  4989.8   87.55  4996.3   83.78
  5004.2   83.43  5010.6   87.47  5054.8   99.71  5095.2  100.52  5099.7    98.4
  6633.2   98.44  6683.3   100.5  6723.3   100.6  6755.3    98.8  6931.3   100.6
#Mann= 8 , 1 , 0
  3058.2      .2       0  3834.7     .14       0  4181.6      .1       0
  4314.1     .14       0  4482.6      .1       0  4950.5     .04       0
  5054.8     .07       0  6633.2      .2       0
#XS Ineff= 2 , 0
       0  3882.2   100.5 5097.37       0    99.5
Permanent Ineff=
       F       F
Bank Sta=4950.5,5054.8
XS Rating Curve= 0
Exp/Cntr=.3,.1

Type RM Length L Ch R = 1 ,1398.1  ,971.4,975,1061.7
BEGIN DESCRIPTION:
Cross Section 1398.1
END DESCRIPTION:
XS GIS Cut Line= 6
      3097276.28     13920810.69      3096787.95     13920248.65
      3095808.15     13919987.74      3095056.57     13919914.86
      3094637.51     13919987.74      3093862.26     13920404.16
#Sta/Elev= 30
  2680.5   100.4  2880.5    97.1  3328.5    99.2  3521.1    98.6  3609.1    96.4
    3783   98.54  3913.1    99.4    4221   96.67  4313.1    95.8  4385.1    98.2
    4647    96.4  4957.1   96.87  5001.2   83.21  5003.8   83.32  5007.5   86.56
  5038.7   93.06  5053.4   98.35    5191   100.2  5291.1   98.75  5779.5    97.7
  5819.5    95.3  5875.5    98.7  5923.5    95.8  6075.5   100.3  6155.5    98.2
  6227.5    99.4  6379.5      98  6403.5    99.2  6451.5   107.5  6499.5   108.3
#Mann= 6 , 1 , 0
  2680.5      .2       0    3783     .14       0    4221      .1       0
  4957.1     .04       0  5053.4     .05       0  5291.1     .14       0
#XS Ineff= 2 , 0
       0  3913.1    99.4  5278.1       0      99
Permanent Ineff=
       F       F
Bank Sta=4957.1,5053.4
XS Rating Curve= 0
Exp/Cntr=.3,.1

Type RM Length L Ch R = 1 ,423.1   ,0,0,0
BEGIN DESCRIPTION:
Cross Section 423.1
END DESCRIPTION:
XS GIS Cut Line= 4
      3095449.62     13918970.41      3095339.67       13918965.
      3095193.22      13918949.2      3095153.75     13918955.78
#Sta/Elev= 23
  4837.5    99.8  4847.5   96.87  4923.7   97.46  4927.5   97.49  4931.7   98.95
  4949.7   97.71  4954.4   97.68  4969.7   92.25  4989.1   86.66  4992.2   83.25
    4994   82.86  4999.3   82.32  5005.3   82.48  5007.9   83.41    5010   85.37
  5029.5    91.1  5049.8   97.18  5060.9   97.11  5081.5   97.48  5087.6    97.5
  5094.9   97.66  5124.9   98.08  5134.9    99.8
#Mann= 4 , 1 , 0
  4837.5      .2       0  4923.7     .06       0  4954.4     .04       0
  5049.8     .07       0
Bank Sta=4954.4,5049.8
XS Rating Curve= 0
Exp/Cntr=.3,.1

Chan Stop Cuts=-1